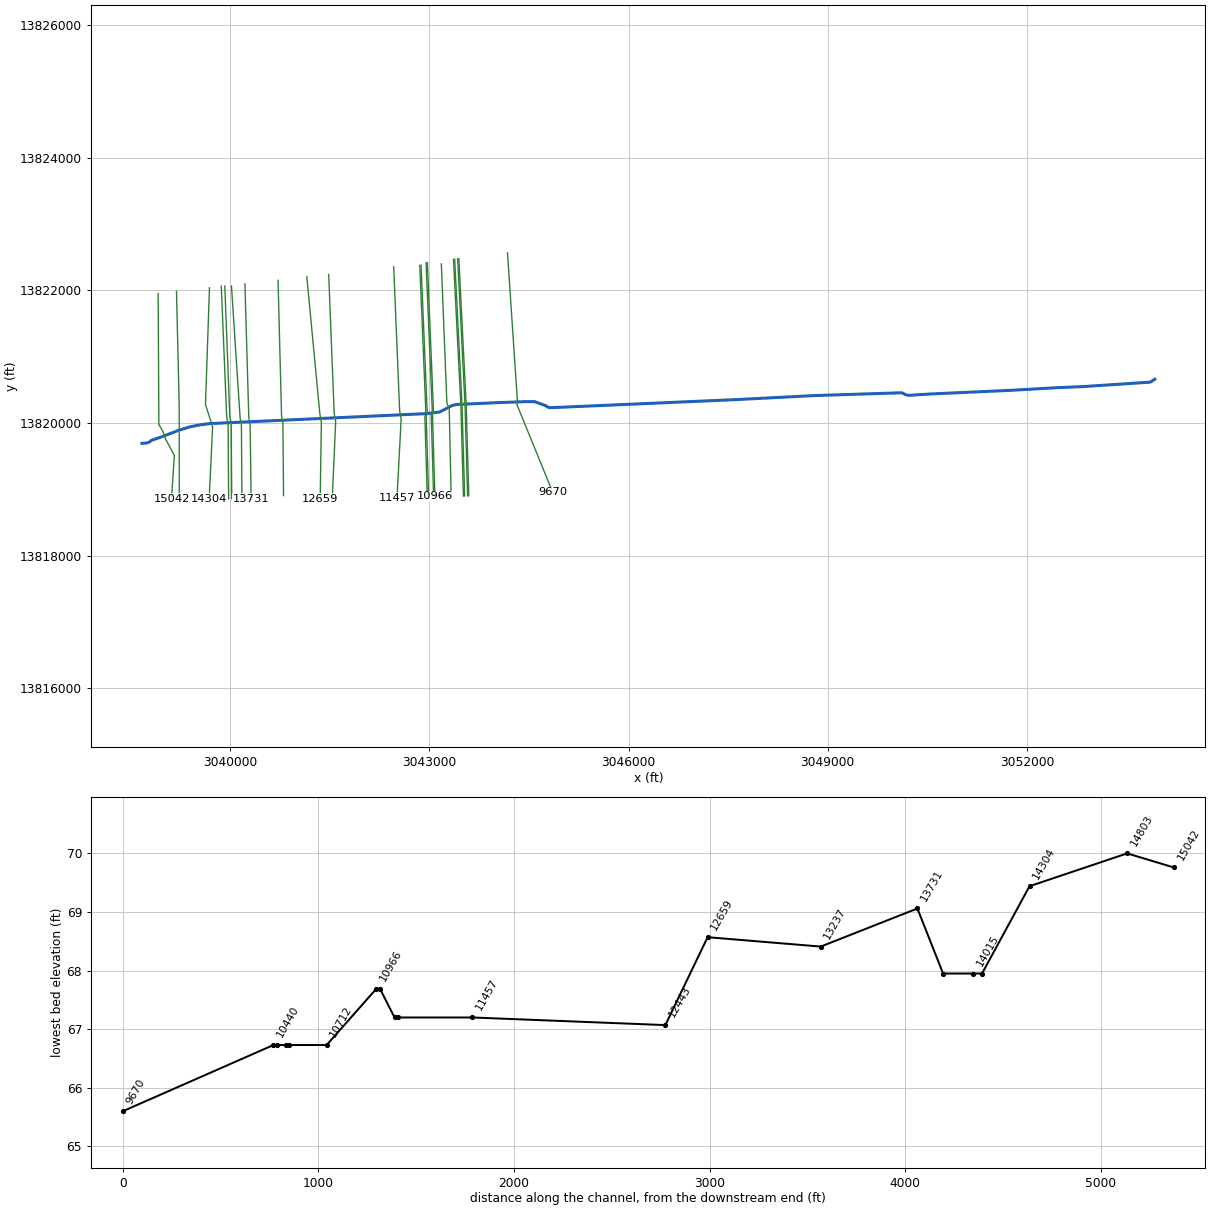
--- D126-00-00.prj (project) ---

Proj Title=D126-00-00
Current Plan=p02
Default Exp/Contr=.3,.1
English Units
Geom File=g02
Flow File=f04
Flow File=f01
Plan File=p03
Plan File=p02
Y Axis Title=Elevation
X Axis Title(PF)=Main Channel Distance
X Axis Title(XS)=Station
BEGIN DESCRIPTION:
Brays Bayou Watershed
Tributary 23.53
HCFCD Unit D126-00-00
Flood Hazard & Floodway Model
10, 2, 1, 0.2% Event
Filename D126.prj
Prepared by: Dodson & Associates, Inc.   Date: September 2003
Reviewed by:____________________	 Date:_________
STATUS (Final RAS)
FOR FLOOD HARZARD RECOVERY DATA ONLY,03/02/2004
Will Be Voided Upon Release of The Preliminary DFIRM
END DESCRIPTION:
DSS File=dss
DSS Export Rating Curves= 0
DSS Export Rating Curve Sorted= 0
DSS Export Volume Flow Curves= 0
DXF OffsetX= 0
DXF OffsetY= 0
DXF ScaleX= 1
DXF ScaleY= 10

--- D126-00-00.p02 (plan) ---

Plan Title=Floodway
Version=Version 3.0.1  Mar 2001
Short Identifier=Floodway0607
Geom File=g02
Flow File=f04
Subcritical Flow
K Sum by GR= 0
Std Step Tol= 0.003
Critical Tol= 0.003
Num of Std Step Trials= 20
Max Error Tol= 0.1
Flow Tol Ratio= 0.001
Split Flow NTrial= 30
Split Flow Tol= 0.02
Split Flow Ratio= 0.02
Log Output Level= 0
Friction Slope Method= 1
Unsteady Friction Slope Method= 2
Parabolic Critical Depth
Global Vel Dist= 0 , 0 , 0
Global Log Level= 0
CheckData=True
Encroach Param=-1 ,0,0, 2
Encroach River=D126-00-00
Encroach Reach=Reach 0
Encroach Node=15042
       1 1709.74 2194.92
Encroach Node=14803
       1 1727.03 2125.89
Encroach Node=14304
       1  1783.1 2096.04
Encroach Node=14062
       1 1906.26 1989.89
Encroach Node=14015
       1 1905.26 1988.89
Encroach Node=13932
       1 1905.26 1988.89
Encroach Node=13863
       1 2005.26 2088.89
Encroach Node=13731
       1 2029.65 2106.79
Encroach Node=13237
       1 2064.73  2139.4
Encroach Node=12659
       1 2101.33 2214.65
Encroach Node=12443
       1 2110.18  2190.5
Encroach Node=11457
       1 2195.68 2272.53
Encroach Node=11078
       1 2193.68 2270.53
Encroach Node=11059
       1 2170.27 2270.53
Encroach Node=11021
       1 2170.27 2270.53
Encroach Node=10984
       1 2229.22  2293.8
Encroach Node=10966
       1 2233.18 2282.05
Encroach Node=10712
       1 2119.34 2179.83
Encroach Node=10521
       1 2141.34 2201.83
Encroach Node=10503
       1 2133.98 2218.86
Encroach Node=10481
       1 2133.98 2218.86
Encroach Node=10458
       1 2133.98 2218.86
Encroach Node=10440
       1 2130.82 2221.06
Encroach Node=9670
       1 2189.56 2279.19
Encroach Node=9192
       1 2324.55 2423.84
Encroach Node=8025
       1  2402.7  2542.5
Encroach Node=7902
       1  2422.7  2566.5
Encroach Node=7807
       1 2427.19 2577.89
Encroach Node=7752
       1 2427.19 2577.89
Encroach Node=7698
       1 2452.98 2577.37
Encroach Node=7604
       1 2448.44 2581.37
Encroach Node=7387
       1 2480.09 2614.41
Encroach Node=7362
       1 2480.09 2614.41
Encroach Node=7337
       1 2480.09 2614.41
Encroach Node=7029
       1 2480.09 2614.41
Encroach Node=6047
       1 2553.91 2689.57
Encroach Node=5905
       1 2553.91 2689.57
Encroach Node=5880
       1 2553.91 2689.57
Encroach Node=5855
       1 2553.91 2689.57
Encroach Node=5805
       1 2553.91 2689.57
Encroach Node=5223
       1 2652.26 2772.73
Encroach Node=5152
       1 2644.16 2769.73
Encroach Node=5117
       1 2644.16 2769.73
Encroach Node=5081
       1 2677.26 2797.73
Encroach Node=5012
       1 1224.28  1350.4
Encroach Node=4867
       1 1238.79 1362.88
Encroach Node=3888
       1 1217.39 1368.95
Encroach Node=3104
       1  1272.8 1402.78
Encroach Node=2803
       1 1294.66 1392.63
Encroach Node=2559
       1 1293.89 1378.93
Encroach Node=2503
       1 1295.89 1380.93
Encroach Node=2467
       1 1295.89 1380.93
Encroach Node=2441
       1 1297.89 1384.42
Encroach Node=2385
       1  435.89  522.42
Encroach Node=2001
       1  400.61  540.73
Encroach Node=1500
       1  413.85  565.16
Encroach Node=1185
       1  396.67  507.79
Encroach Node=1166
       1  395.67  506.79
Encroach Node=630
       1  395.67  506.79
Encroach Node=80
       1  360.57  454.79
Encroach Reach=D126-00-00_0001
Encroach Node=15042
       1 1709.74 2194.92
Encroach Node=14803
       1 1727.03 2125.89
Encroach Node=14304
       1  1783.1 2096.04
Encroach Node=14062
       1 1906.26 1989.89
Encroach Node=14015
       1 1905.26 1988.89
Encroach Node=13932
       1 1905.26 1988.89
Encroach Node=13863
       1 2005.26 2088.89
Encroach Node=13731
       1 2029.65 2106.79
Encroach Node=13237
       1 2064.73  2139.4
Encroach Node=12659
       1 2101.33 2214.65
Encroach Node=12443
       1 2110.18  2190.5
Encroach Node=11457
       1 2195.68 2272.53
Encroach Node=11078
       1 2193.68 2270.53
Encroach Node=11059
       1 2170.27 2270.53
Encroach Node=11021
       1 2170.27 2270.53
Encroach Node=10984
       1 2229.22  2293.8
Encroach Node=10966
       1 2233.18 2282.05
Encroach Node=10712
       1 2119.34 2179.83
Encroach Node=10521
       1 2141.34 2201.83
Encroach Node=10503
       1 2133.98 2218.86
Encroach Node=10481
       1 2133.98 2218.86
Encroach Node=10458
       1 2133.98 2218.86
Encroach Node=10440
       1 2130.82 2221.06
Encroach Node=9670
       1 2189.56 2279.19
Encroach Node=9192
       1 2324.55 2423.84
Encroach Node=8025
       1  2402.7  2542.5
Encroach Node=7902
       1  2422.7  2566.5
Encroach Node=7807
       1 2427.19 2577.89
Encroach Node=7752
       1 2427.19 2577.89
Encroach Node=7698
       1 2452.98 2577.37
Encroach Node=7604
       1 2448.44 2581.37
Encroach Node=7387
       1 2480.09 2614.41
Encroach Node=7362
       1 2480.09 2614.41
Encroach Node=7337
       1 2480.09 2614.41
Encroach Node=7029
       1 2480.09 2614.41
Encroach Node=6047
       1 2553.91 2689.57
Encroach Node=5905
       1 2553.91 2689.57
Encroach Node=5880
       1 2553.91 2689.57
Encroach Node=5855
       1 2553.91 2689.57
Encroach Node=5805
       1 2553.91 2689.57
Encroach Node=5223
       1 2652.26 2772.73
Encroach Node=5152
       1 2644.16 2769.73
Encroach Node=5117
       1 2644.16 2769.73
Encroach Node=5081
       1 2677.26 2797.73
Encroach Node=5012
       1 1224.28  1350.4
Encroach Node=4867
       1 1238.79 1362.88
Encroach Node=3888
       1 1217.39 1368.95
Encroach Node=3104
       1  1272.8 1402.78
Encroach Node=2803
       1 1294.66 1392.63
Encroach Node=2559
       1 1293.89 1378.93
Encroach Node=2503
       1 1295.89 1380.93
Encroach Node=2467
       1 1295.89 1380.93
Encroach Node=2441
       1 1297.89 1384.42
Encroach Node=2385
       1  435.89  522.42
Encroach Node=2001
       1  400.61  540.73
Encroach Node=1500
       1  413.85  565.16
Encroach Node=1185
       1  396.67  507.79
Encroach Node=1166
       1  395.67  506.79
Encroach Node=630
       1  395.67  506.79
Encroach Node=80
       1  360.57  454.79
Computation Interval=1HOUR
Output Interval=1HOUR
Run HTab= 0
Run UNet= 0
Run PostProcess= 0
UNET Theta= 1
UNET ZTol= 0.02
UNET ZSATol= 0.1
UNET MxIter= 20
UNET MaxInSteps= 20
UNET DtIC= 0
UNET DtMin= 0
UNET MaxCRTS= 20
UNET WFStab= 2
UNET SFStab= 1
UNET WFX= 1
UNET SFX= 1
UNET Convert EG Bridges=-1
UNET Use Existing IB Tables=-1
Instantaneous Interval=1HOUR
Write IC File= 0
Write Velocity= 0
Write Detailed= 0

--- D126-00-00.p03 (plan) ---

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Plan Title=FEMA Effective June 2007
Short Identifier=FEMAeff0607
Geom File=g02
Flow File=f01
       1    1708 2194.92
       1 2197.02 2272.53

--- D126-00-00.f04 (steady flow) ---

Flow Title=Floodway
Version=Version 3.0.1  Mar 2001
Number of Profiles= 2
Profile Names=1PCT_100yr,1PCTFloodway_100yrFW
River Rch & RM=D126-00-00,D126-00-00_0001 ,15042
     298     298
River Rch & RM=D126-00-00,D126-00-00_0001 ,14304
     320     320
River Rch & RM=D126-00-00,D126-00-00_0001 ,13731
     374     374
River Rch & RM=D126-00-00,D126-00-00_0001 ,12443
     447     447
River Rch & RM=D126-00-00,D126-00-00_0001 ,10966
     522     522
River Rch & RM=D126-00-00,D126-00-00_0001 ,9670
     670     670
River Rch & RM=D126-00-00,D126-00-00_0001 ,7604
     809     809
River Rch & RM=D126-00-00,D126-00-00_0001 ,6047
     933     933
River Rch & RM=D126-00-00,D126-00-00_0001 ,4867
    1050    1050
River Rch & RM=D126-00-00,D126-00-00_0001 ,3888
    1154    1154
River Rch & RM=D126-00-00,D126-00-00_0001 ,3104
    1259    1259
River Rch & RM=D126-00-00,D126-00-00_0001 ,2385
    1458    1458
River Rch & RM=D126-00-00,D126-00-00_0001 ,1166
    1679    1679
Boundary for River Rch & Prof#=D126-00-00,D126-00-00_0001 , 1
Up Type= 0
Dn Type= 1
Dn Known WS=67.06
Boundary for River Rch & Prof#=D126-00-00,D126-00-00_0001 , 2
Up Type= 0
Dn Type= 1
Dn Known WS=67.06
DSS Import GetInterval= 0
DSS Import GetPeak= 0
DSS Import FillOption= 0

--- D126-00-00.f01 (steady flow) ---

Flow Title=FEMA Effective June 2007
Version=Version 3.0.1  Mar 2001
Number of Profiles= 4
Profile Names=10PCT_10yr,2PCT_50yr,1PCT_100yr,0.2PCT_500yr
River Rch & RM=D126-00-00,D126-00-00_0001 ,15042
     182     255     298     427
River Rch & RM=D126-00-00,D126-00-00_0001 ,14304
     195     273     320     457
River Rch & RM=D126-00-00,D126-00-00_0001 ,13731
     227     319     374     532
River Rch & RM=D126-00-00,D126-00-00_0001 ,12443
     271     382     447     634
River Rch & RM=D126-00-00,D126-00-00_0001 ,10966
     315     447     522     739
River Rch & RM=D126-00-00,D126-00-00_0001 ,9670
     403     575     670     945
River Rch & RM=D126-00-00,D126-00-00_0001 ,7604
     484     694     809    1136
River Rch & RM=D126-00-00,D126-00-00_0001 ,6047
     557     801     933    1307
River Rch & RM=D126-00-00,D126-00-00_0001 ,4867
     625     903    1050    1468
River Rch & RM=D126-00-00,D126-00-00_0001 ,3888
     686     993    1154    1611
River Rch & RM=D126-00-00,D126-00-00_0001 ,3104
     747    1083    1259    1754
River Rch & RM=D126-00-00,D126-00-00_0001 ,2385
     863    1256    1458    2027
River Rch & RM=D126-00-00,D126-00-00_0001 ,1166
     991    1447    1679    2328
Boundary for River Rch & Prof#=D126-00-00,D126-00-00_0001 , 1
Up Type= 0
Dn Type= 3
Dn Slope=.0007
Boundary for River Rch & Prof#=D126-00-00,D126-00-00_0001 , 2
Up Type= 0
Dn Type= 3
Dn Slope=.0007
Boundary for River Rch & Prof#=D126-00-00,D126-00-00_0001 , 3
Up Type= 0
Dn Type= 3
Dn Slope=.0007
Boundary for River Rch & Prof#=D126-00-00,D126-00-00_0001 , 4
Up Type= 0
Dn Type= 3
Dn Slope=.0007
DSS Import GetInterval= 0
DSS Import GetPeak= 0
DSS Import FillOption= 0

--- D126-00-00.g02 (geometry) ---

Geom Title=D126-00-00 June 2007
Version=Version 3.0.1  Mar 2001

River Reach=D126-00-00      ,D126-00-00_0001
Reach XY= 30
     3038669.319     13819692.92     3038744.333    13819698.747
     3038787.677    13819715.715     3038805.106    13819735.028
     3038989.698    13819799.796     3039220.932    13819889.068
     3039395.067    13819942.248     3039519.077    13819967.063
      3039680.03    13819990.102      3042951.21    13820140.546
     3043152.591    13820165.672     3043346.505    13820264.066
      3043404.74     13820278.12     3044011.349     13820305.75
     3044471.136    13820322.118     3044585.449    13820320.654
     3044746.898    13820262.699     3044784.241    13820238.848
     3044828.913    13820230.106     3047608.564     13820351.49
     3048803.035    13820413.146     3050115.709    13820455.124
      3050176.22    13820425.103     3050217.217    13820416.171
     3050551.481    13820437.107      3051768.39    13820492.554
     3052455.486    13820531.702     3052848.935    13820548.328
     3053858.893    13820615.188     3053926.925    13820659.418

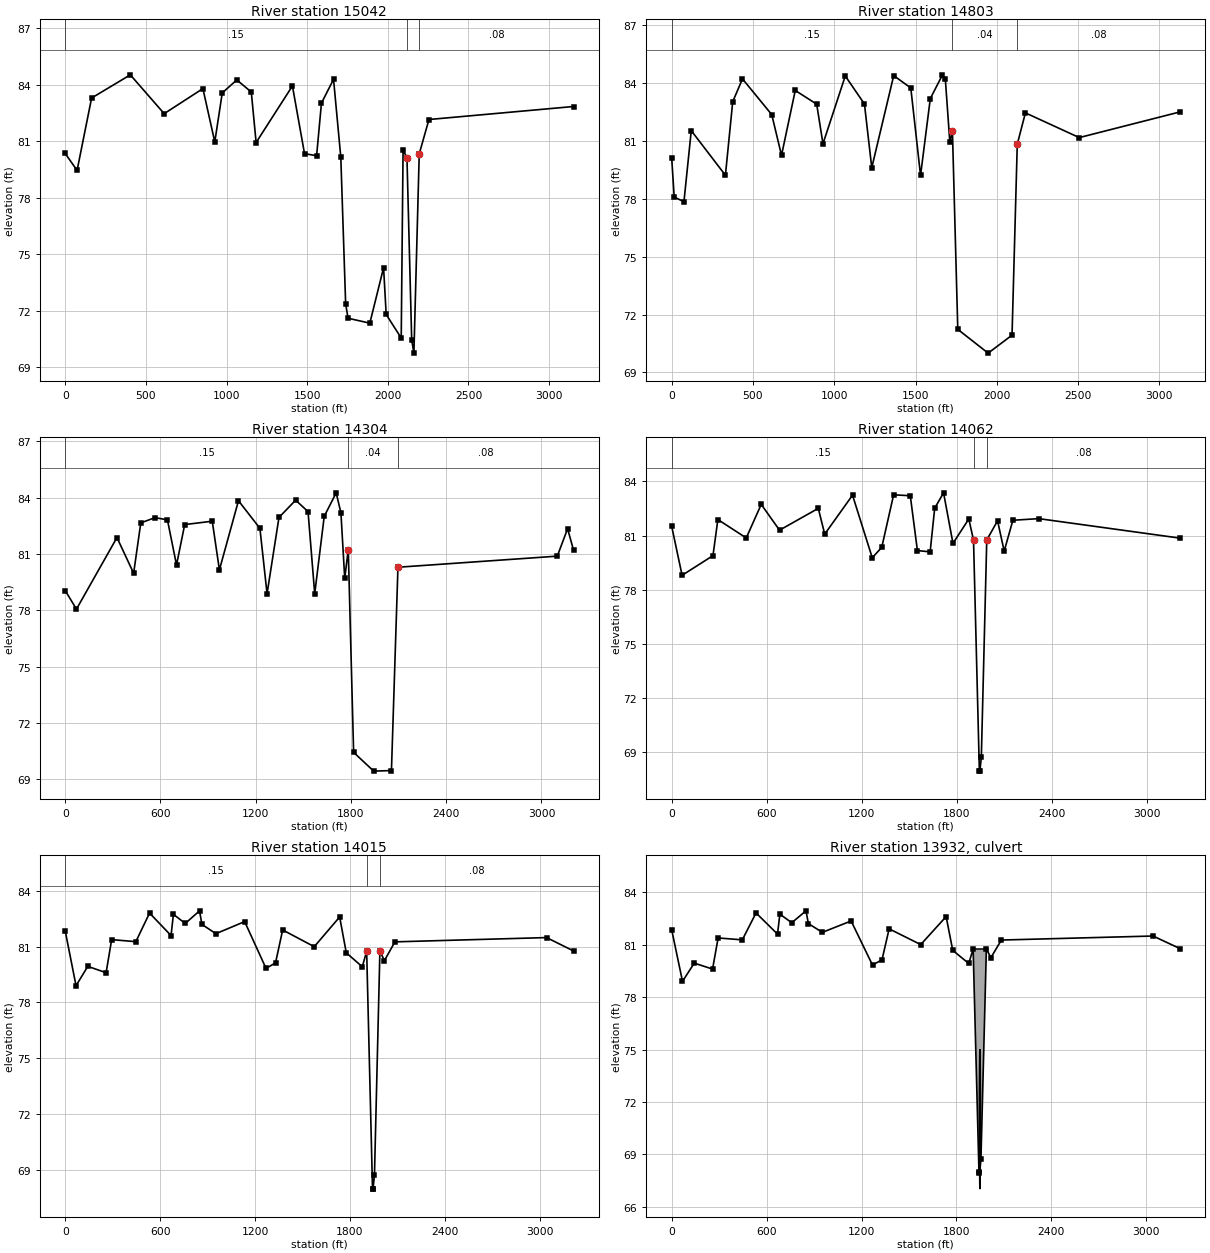
Type RM Length L Ch R = 1 ,15042   ,306.55,238.99,171.01
BEGIN DESCRIPTION:
15028  Surveyed cross-section/detention basin in left overbank
END DESCRIPTION:
XS GIS Cut Line= 6
     3038913.803    13821951.122     3038924.415    13819977.328
     3038984.672    13819872.541     3039022.436    13819764.018
     3039157.874    13819510.409     3039114.342    13818857.434
#Sta/Elev= 30
       0   80.35   73.62   79.45  163.62   83.29  403.63   84.52  613.63   82.46
  853.63   83.79  927.35   80.96  973.64   83.56 1063.64   84.25 1153.64   83.61
 1183.64   80.93 1408.64   83.93 1483.64   80.34 1558.64   80.23 1588.64   83.02
 1663.65   84.28 1708.65   80.15 1738.65   72.38 1753.65   71.61 1888.65   71.35
 1973.82   74.29 1990.04   71.81 2083.21   70.56  2094.7   80.53 2118.74   80.13
 2148.17   70.46 2161.83   69.76 2194.92   80.33 2255.11   82.15 3151.54   82.84
#Mann= 3 , 0 , 0
       0     .15       0 2118.74     .04       0 2194.92     .08       0
#XS Ineff= 2 , 0
       0    1693            2926       0
Permanent Ineff=
       T       T
Bank Sta=2118.74,2194.92
XS Rating Curve= 0
Exp/Cntr=.3,.1

Type RM Length L Ch R = 1 ,14803   ,449.56,499.05,513.32
BEGIN DESCRIPTION:
14789  Surveyed cross-section/channel cross-section includes detention basin in left overbank area
END DESCRIPTION:
XS GIS Cut Line= 4
      3039189.71    13821982.957     3039230.775    13820272.392
     3039230.775    13819840.536      3039231.98     13818856.56
#Sta/Elev= 30
       0   80.12   15.46   78.08   75.48   77.84  120.49   81.52  330.55   79.21
  375.57   83.02  435.58    84.2  615.63   82.35  675.65   80.24  760.22    83.6
  892.09   82.89  930.73   80.84 1067.92   84.35  1185.8    82.9 1230.81    79.6
 1365.85   84.37 1470.88   83.73  1530.9    79.2 1590.92   83.18 1665.94   84.41
 1683.33   84.19 1711.06   80.92 1727.03    81.5 1759.97   71.23 1946.72      70
 2093.67   70.93 2125.89   80.82 2175.95   82.44 2507.23   81.16 3126.89   82.49
#Mann= 3 , 0 , 0
       0     .15       0 1727.03     .04       0 2125.89     .08       0
#XS Ineff= 2 , 0
       0    1719            2822       0
Permanent Ineff=
       T       T
Bank Sta=1727.03,2125.89
XS Rating Curve= 0
Exp/Cntr=.3,.1

Type RM Length L Ch R = 1 ,14304   ,275.54,242.63,239.58
BEGIN DESCRIPTION:
14290  Surveyed cross-section/channel cross-section includes detention basin in left overbank area
END DESCRIPTION:
XS GIS Cut Line= 4
     3039686.678    13822038.294     3039626.639    13820278.603
     3039733.866    13819942.988     3039682.465    13818855.136
#Sta/Elev= 30
       0   79.05   70.84   78.06  325.98   81.87  431.04   79.97  476.07   82.65
  566.12   82.93  643.95   82.81   701.2   80.41  752.72   82.56  926.33   82.74
  971.36   80.15 1091.43   83.83 1226.51   82.36 1271.53   78.88 1346.58   82.94
 1451.64   83.86 1529.67   83.25 1571.71   78.88 1631.74      83 1706.79   84.25
  1736.8   83.19 1760.72    79.7  1783.1   81.23 1816.77   70.44 1943.41   69.44
 2055.11   69.47 2096.04   80.29 3099.84   80.88  3164.7   82.34 3202.11    81.2
#Mann= 3 , 0 , 0
       0     .15       0  1783.1     .04       0 2096.04     .08       0
#XS Ineff= 2 , 0
       0    1757            2503       0
Permanent Ineff=
       T       T
Bank Sta=1783.1,2096.04
XS Rating Curve= 0
Exp/Cntr=.3,.1

Type RM Length L Ch R = 1 ,14062   ,47.28,46.68,47.12
BEGIN DESCRIPTION:
14048  Copied surveyed cross-section XS4
END DESCRIPTION:
XS GIS Cut Line= 6
     3039864.618    13822063.111     3039946.713    13820082.374
     3039959.993    13820028.274     3039958.623    13820015.374
     3039967.573    13819963.474     3039975.355     13818857.12
#Sta/Elev= 30
       0   81.52   65.67    78.8  260.83   79.89  291.67   81.89  471.02   80.87
  565.56   82.73   681.2    81.3  925.94   82.51  966.44   81.08 1142.17   83.24
  1266.7   79.77 1326.75   80.35 1401.65   83.26  1506.9   83.21 1551.94   80.17
  1632.3    80.1 1661.13   82.52 1717.08   83.37 1776.45   80.57 1876.48   81.92
 1906.26   80.75 1943.15   67.98 1946.35   67.95  1955.6   68.72 1989.89   80.76
 2058.18   81.82 2099.89   80.14 2154.84   81.85 2318.27   81.94 3210.25   80.86
#Mann= 3 , 0 , 0
       0     .15       0 1906.26     .04       0 1989.89     .08       0
#XS Ineff= 2 , 0
       0    1899            2308       0
Permanent Ineff=
       T       T
Bank Sta=1906.26,1989.89
XS Rating Curve= 0
Exp/Cntr=.5,.3

Type RM Length L Ch R = 1 ,14015   ,151.37,152.37,153.75
BEGIN DESCRIPTION:
14001  Copied surveyed cross-section XS3
END DESCRIPTION:
XS GIS Cut Line= 6
      3039917.66    13822065.834     3039993.711    13820082.374
     3040007.001    13820028.274     3040005.621    13820015.374
     3040014.581    13819963.474     3040022.362    13818857.172
#Sta/Elev= 30
       0   81.85   68.38    78.9  142.81   79.94  258.46    79.6  293.55   81.38
   446.4   81.27  533.14   82.81  668.83    81.6  683.84   82.74  758.89   82.25
  848.96   82.93  863.97    82.2  952.38    81.7 1134.17   82.35 1269.27   79.83
 1329.31   80.13 1374.34    81.9 1574.02      81 1734.61    82.6 1776.42   80.67
 1877.61   79.92 1905.26   80.75 1942.15   67.98 1945.35   67.95  1954.6   68.72
 1988.89   80.76 2017.37   80.25 2083.76   81.26 3042.35   81.49 3212.68   80.77
#Mann= 3 , 0 , 0
       0     .15       0 1905.26     .04       0 1988.89     .08       0
#XS Ineff= 2 , 0
       0    1900            2269       0
Permanent Ineff=
       T       T
Bank Sta=1905.26,1988.89
XS Rating Curve= 0
Exp/Cntr=.5,.3

Type RM Length L Ch R = 2 ,13932   ,,,
BEGIN DESCRIPTION:
13918  Eldridge Culvert
END DESCRIPTION:
Bridge Culvert--1,0,-1,-1, 0
Deck Dist Width WeirC Skew NumUp NumDn MinLoCord MaxHiCord MaxSubmerge Is_Ogee
11.185,130,2.6,0, 2, 2, , , .95, 0, 0,0,,
 1905.28 2001.34
   80.74   80.74
                
 1994.74 2101.34
   80.74   80.74
                
BR Coef=-1 , 0 , 0 ,, 0 ,,,.8,-1,,0,
WSPro=,,,, 1 ,,,, 0 ,,,, 0 ,,,,-1 ,-1 ,-1 , 0 , 0 , 0 , 0 , 0
Culvert=1,8,,130,.012,.2,1,1,2,67.02,1948.04,67.02,2048.04,Culvert #1  , 0 ,11.185
Culvert Bottom n=.012
BC Design=,, 0 ,, 0 ,,,,,,

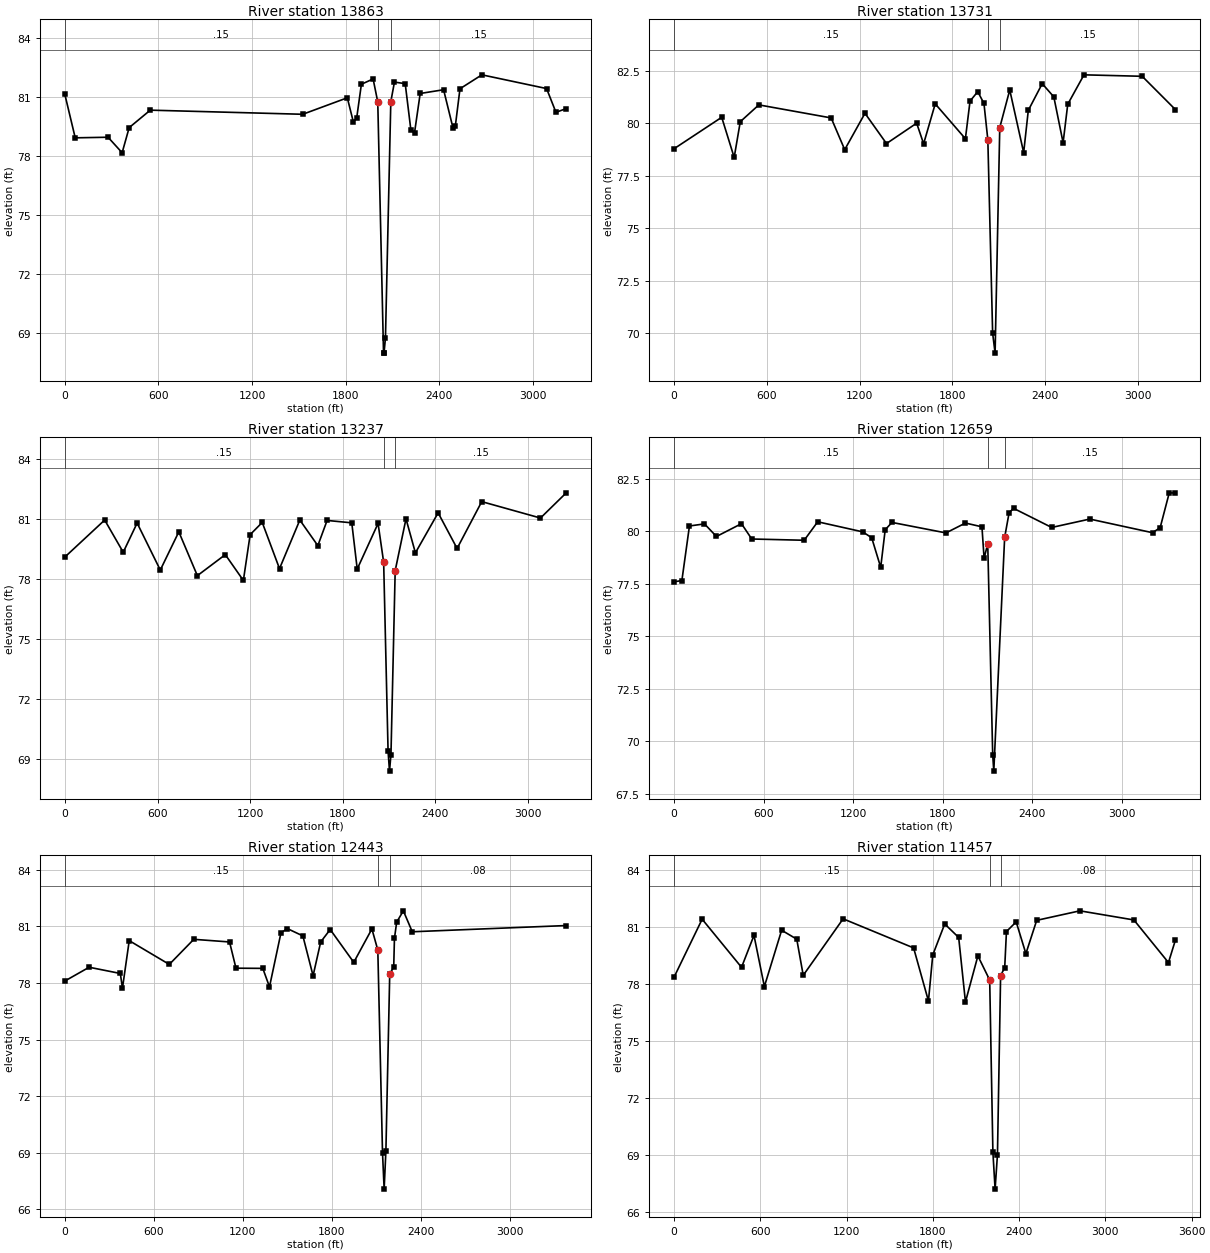
Type RM Length L Ch R = 1 ,13863   ,135.23,131.48,132.18
BEGIN DESCRIPTION:
13849  Surveyed cross-section/XS2
END DESCRIPTION:
XS GIS Cut Line= 4
     3040018.006    13822063.752      3040147.95    13820081.415
     3040167.952    13819962.405     3040176.206    13818856.481
#Sta/Elev= 30
       0   81.13   66.39   78.92  276.84   78.95  367.04   78.16  412.13   79.44
  547.42   80.33 1524.52   80.12 1810.13   80.96 1848.78   79.73 1870.26   79.93
 1900.32   81.65 1975.48   81.92 2005.26   80.75 2042.15   67.98 2045.35   67.95
  2054.6   68.72 2088.89   80.76 2112.18   81.76 2181.17   81.68 2217.18   79.34
 2240.73   79.17 2277.18   81.18 2427.18   81.37 2487.19   79.43 2502.19   79.51
 2532.19   81.42 2672.52   82.13  3087.2   81.43 3147.21   80.22 3213.23   80.41
#Mann= 3 , 0 , 0
       0     .15       0 2005.26     .04       0 2088.89     .15       0
#XS Ineff= 2 , 0
       0    1991            2126       0
Permanent Ineff=
       T       T
Bank Sta=2005.26,2088.89
XS Rating Curve= 0
Exp/Cntr=.5,.3

Type RM Length L Ch R = 1 ,13731   ,495.63,493.92,494.42
BEGIN DESCRIPTION:
13717  Surveyed cross-section/XS1
END DESCRIPTION:
XS GIS Cut Line= 4
      3040220.64    13822096.238     3040279.042    13820087.242
     3040299.336    13819969.397     3040313.901    13818856.856
#Sta/Elev= 30
       0   78.78  308.87   80.28  389.45   78.37  428.92   80.07  548.97   80.87
 1016.49   80.25  1104.2   78.74 1235.23   80.47 1374.32   79.03  1569.4      80
 1614.42   79.02 1689.45   80.92 1884.53   79.26 1914.55   81.05 1964.35    81.5
 2004.58   80.94 2029.65   79.21 2060.69   70.01 2076.61   69.06 2106.79   79.79
 2171.33   81.58 2261.33    78.6 2291.33   80.61 2381.34   81.88 2456.35   81.25
 2516.35   79.07 2546.36    80.9 2651.37    82.3  3027.8   82.23 3242.06   80.65
#Mann= 3 , 0 , 0
       0     .15       0 2029.65     .04       0 2106.79     .15       0
#XS Ineff= 2 , 0
       0    2019            2132       0
Permanent Ineff=
       T       T
Bank Sta=2029.65,2106.79
XS Rating Curve= 0
Exp/Cntr=.3,.1

Type RM Length L Ch R = 1 ,13237   ,567.72,578.29,576.46
BEGIN DESCRIPTION:
13223  Surveyed cross-section
END DESCRIPTION:
XS GIS Cut Line= 4
     3040719.726    13822150.396     3040772.506     13820110.12
     3040792.968    13819990.322     3040802.702    13818905.537
#Sta/Elev= 30
       0   79.11  257.98   80.96  378.02   79.35  468.05   80.81   618.1   78.46
  738.14   80.37  858.18   78.18 1039.15   79.23 1156.16   77.94 1200.04   80.23
 1278.32   80.84 1390.18   78.53 1521.82   80.96 1638.44   79.68 1698.46   80.94
 1858.24   80.82 1893.53   78.51 2028.57   80.79 2064.73   78.85 2093.36    69.4
 2102.59   68.41 2112.09   69.24  2139.4   78.43 2209.43   81.02 2270.32   79.32
 2417.57   81.32 2540.33   79.54 2700.04   81.88 3080.35   81.06 3247.32   82.32
#Mann= 3 , 0 , 0
       0     .15       0 2064.73     .04       0  2139.4     .15       0
#XS Ineff= 2 , 0
       0    2050            2166       0
Permanent Ineff=
       T       T
Bank Sta=2064.73,2139.4
XS Rating Curve= 0
Exp/Cntr=.3,.1

Type RM Length L Ch R = 1 ,12659   ,226.82,215.98,211.09
BEGIN DESCRIPTION:
12645  Surveyed cross-section
END DESCRIPTION:
XS GIS Cut Line= 4
     3041152.892    13822205.805     3041349.416    13820138.208
     3041372.248    13820010.204     3041354.777    13818859.691
#Sta/Elev= 30
       0   77.59   53.12   77.65  103.77   80.25  204.48   80.35  284.58   79.75
  452.16   80.36  520.96   79.63  872.22   79.57  962.62   80.45 1264.05   79.97
 1324.25   79.69 1384.52   78.28 1414.65   80.07 1459.86   80.42 1821.48   79.92
 1951.97   80.39 2062.56   80.21 2076.92   78.71 2101.33    79.4 2134.61   69.34
 2141.85   68.57 2214.65   79.71 2244.65   80.89 2274.65   81.09 2529.68   80.18
 2784.71   80.58 3204.76   79.93 3255.95   80.17 3316.88   81.83 3357.59   81.82
#Mann= 3 , 0 , 0
       0     .15       0 2101.33     .04       0 2214.65     .15       0
#XS Ineff= 2 , 0
       0    2084            2240       0
Permanent Ineff=
       T       T
Bank Sta=2101.33,2214.65
XS Rating Curve= 0
Exp/Cntr=.3,.1

Type RM Length L Ch R = 1 ,12443   ,990.11,986.04,991
BEGIN DESCRIPTION:
12429  Surveyed cross-section
END DESCRIPTION:
XS GIS Cut Line= 4
     3041482.748    13822236.163     3041565.283    13820146.603
     3041587.787    13820022.399     3041536.619    13818860.186
#Sta/Elev= 30
       0    78.1  163.79   78.83  373.95    78.5  388.39   77.72     434   80.24
  704.21   78.98  869.34   80.31 1110.45   80.17 1153.78   78.78  1334.7   78.77
 1379.74   77.79 1457.04   80.65 1499.83   80.88 1604.91   80.49 1673.66   78.38
 1725.01   80.17 1789.19   80.83 1948.05   79.09 2070.28   80.86 2110.18   79.74
 2141.79   69.01 2152.82   67.07 2164.71    69.1  2190.5   78.47 2217.42   78.84
 2222.32   80.36 2237.33   81.22 2282.38   81.82 2342.44   80.71 3380.75   81.04
#Mann= 3 , 0 , 0
       0     .15       0 2110.18     .04       0  2190.5     .08       0
#XS Ineff= 2 , 0
       0    2096            2423       0
Permanent Ineff=
       T       T
Bank Sta=2110.18,2190.5
XS Rating Curve= 0
Exp/Cntr=.3,.1

Type RM Length L Ch R = 1 ,11457   ,394.42,378.98,370.69
BEGIN DESCRIPTION:
11443  Surveyed cross-section
END DESCRIPTION:
XS GIS Cut Line= 4
     3042461.759    13822355.754     3042551.484    13820184.217
     3042574.232    13820059.653     3042511.799    13818874.759
#Sta/Elev= 30
       0   78.33  196.07   81.39  469.99   78.86   556.5   80.54  628.79   77.85
  748.89   80.81  853.98   80.34  899.02   78.44 1176.43   81.41 1666.61   79.88
 1769.76   77.09 1799.79   79.51 1882.87   81.14 1979.94   80.43 2027.04   77.04
 2113.54   79.46 2195.68   78.19  2217.9   69.15 2233.22    67.2 2249.68   69.02
 2271.54   78.43 2300.01   78.84 2312.18   80.74 2379.74   81.25 2447.37   79.58
 2522.45   81.33 2822.89   81.83 3198.41   81.35 3438.74   79.11 3486.55   80.28
#Mann= 3 , 0 , 0
       0     .15       0 2195.68     .04       0 2271.54     .08       0
#XS Ineff= 2 , 0
       0    2176            2925       0
Permanent Ineff=
       T       T
Bank Sta=2195.68,2271.54
XS Rating Curve= 0
Exp/Cntr=.3,.1

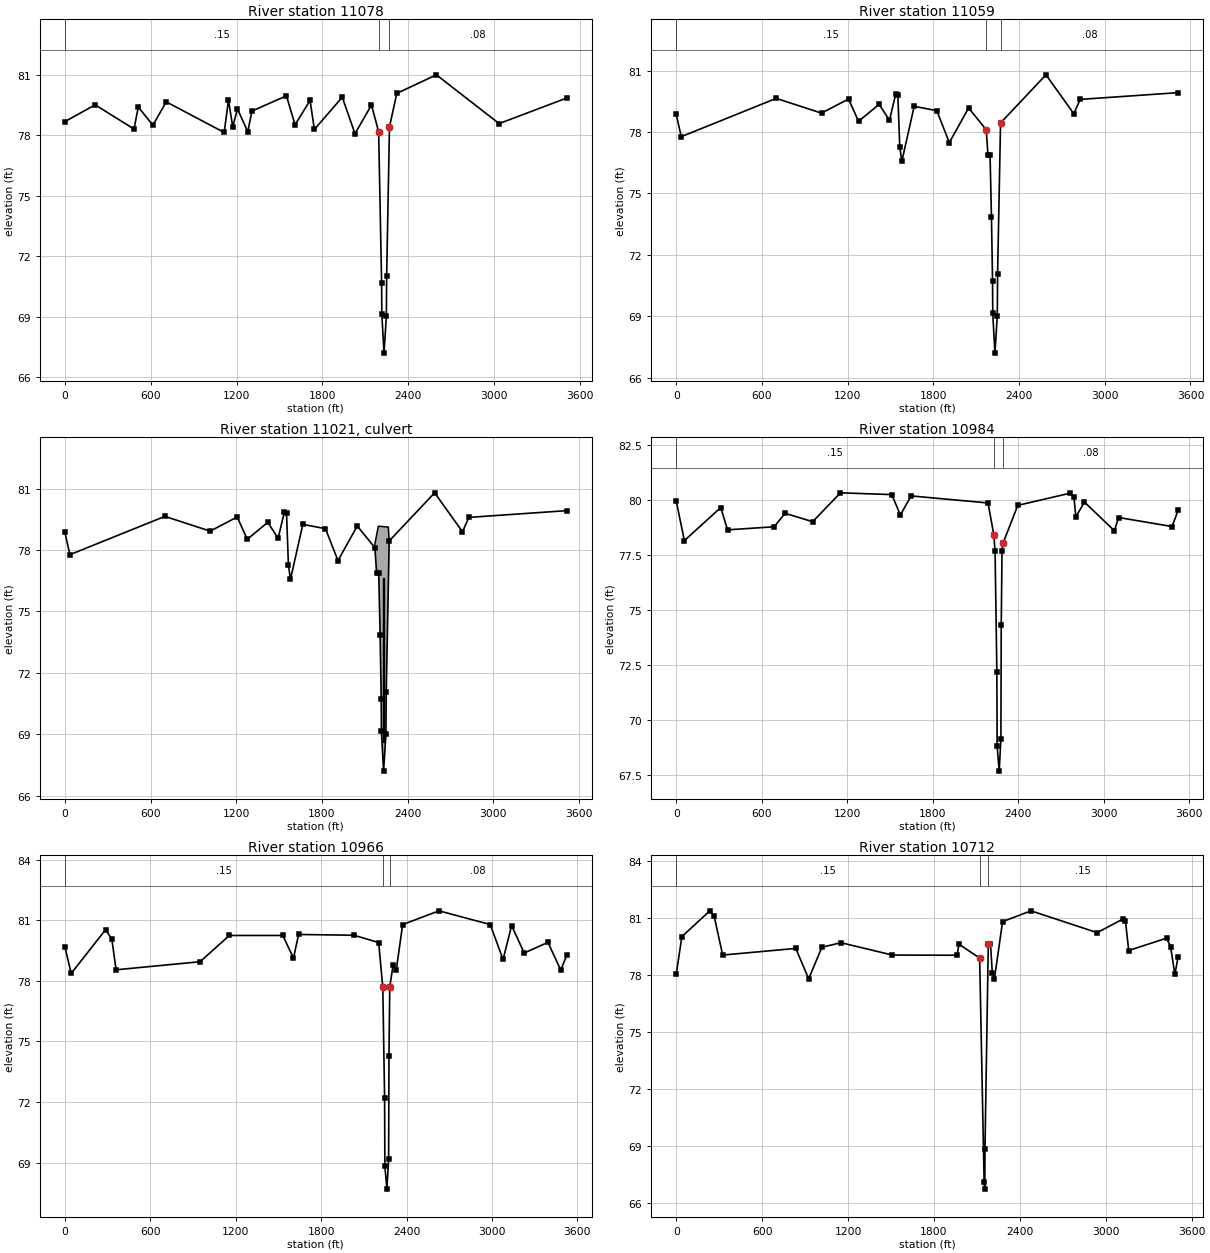
Type RM Length L Ch R = 1 ,11078   ,19.86,19.23,20.17
BEGIN DESCRIPTION:
11064  Copied surveyed cross-section 10970/XS4
END DESCRIPTION:
XS GIS Cut Line= 6
     3042854.684      13822375.3      3042946.16      13820168.4
      3042941.33      13820141.2      3042936.02      13820110.9
      3042931.85      13820087.3      3042968.57      13818869.6
#Sta/Elev= 30
       0   78.69  212.02   79.52  483.21   78.32  513.24   79.41  615.65   78.51
  708.41   79.67 1113.76   78.15 1143.78   79.75 1173.81   78.43 1206.68   79.32
  1278.9   78.18 1307.58   79.21 1549.13   79.97 1609.18   78.53 1714.27   79.74
  1744.3    78.3 1939.46    79.9 2028.35   78.09 2143.68   79.51 2193.68   78.19
 2214.53    70.7  2215.9   69.15 2231.22    67.2 2247.68   69.02 2249.78   71.05
 2269.54   78.43 2320.72   80.09  2597.5   81.01 3036.29   78.59  3509.4   79.86
#Mann= 3 , 0 , 0
       0     .15       0 2193.68     .04       0 2269.54     .08       0
#XS Ineff= 2 , 0
       0    2176            2575       0
Permanent Ineff=
       T       T
Bank Sta=2193.68,2269.54
XS Rating Curve= 0
Exp/Cntr=.5,.3

Type RM Length L Ch R = 1 ,11059   ,77.46,74.54,77.32
BEGIN DESCRIPTION:
11045  Copied surveyed cross-section 10970/XS3
END DESCRIPTION:
XS GIS Cut Line= 6
     3042874.448    13822377.715      3042965.82      13820172.7
       3042964.6      13820165.7      3042962.04      13820151.3
      3042951.67      13820092.3       3042988.6      13818867.5
#Sta/Elev= 30
       0   78.86   35.25   77.77  699.89   79.64 1017.03   78.92 1206.25   79.61
 1276.51   78.52 1420.67   79.35 1492.74   78.57 1536.53   79.85 1551.55   79.79
 1564.82   77.29 1579.24   76.56 1665.73   79.25  1824.3   79.04 1911.86   77.48
 2046.97   79.17 2170.27   78.11 2182.09   76.89  2197.1   76.87 2206.91   73.85
 2214.53    70.7  2215.9   69.15 2231.22    67.2 2247.68   69.02 2249.78   71.05
 2270.53   78.44 2588.48   80.79 2783.57   78.89 2828.16   79.59  3513.9   79.92
#Mann= 3 , 0 , 0
       0     .15       0 2170.27     .04       0 2270.53     .08       0
#XS Ineff= 2 , 0
       0    2177            2549       0
Permanent Ineff=
       T       T
Bank Sta=2170.27,2270.53
XS Rating Curve= 0
Exp/Cntr=.5,.3

Type RM Length L Ch R = 2 ,11021   ,,,
BEGIN DESCRIPTION:
11007  Synott culvert
END DESCRIPTION:
Bridge Culvert--1,0,-1,-1, 0
Deck Dist Width WeirC Skew NumUp NumDn MinLoCord MaxHiCord MaxSubmerge Is_Ogee
7.27,60,2.6,0, 4, 4, , , .95, 0, 0,0,,
 2167.07 2194.18 2264.13 2270.54
   78.18   79.16   79.12   78.46
                                
 2223.07 2230.05    2300 2310.35
   78.93   79.16   79.12   78.78
                                
BR Coef=-1 , 0 , 0 ,, 0 ,,,.8,-1,,0,
WSPro=,,,, 1 ,,,, 0 ,,,, 0 ,,,,-1 ,-1 ,-1 , 0 , 0 , 0 , 0 , 0
Culvert=2,8,9,60,.012,.5,1,8,3,68.63,2229.16,68.63,2265.03,Culvert #1  , 0 ,7.27
Culvert Bottom n=.012
BC Design=,, 0 ,, 0 ,,,,,,

Type RM Length L Ch R = 1 ,10984   ,18.29,18.66,18.85
BEGIN DESCRIPTION:
10970  Surveyed cross-section/XS2
END DESCRIPTION:
XS GIS Cut Line= 4
     3042949.508    13822414.522     3043042.586    13820193.388
     3043027.765    13820112.347     3043063.015    13818894.925
#Sta/Elev= 30
       0   79.95   57.07   78.15   312.3   79.65  360.25   78.64  687.62   78.78
  763.71   79.39  957.86   79.01 1153.03   80.32 1513.35   80.24  1573.4   79.31
 1648.47   80.18 2188.94   79.86 2229.22   78.42 2238.18   77.68 2250.74    72.2
 2252.67   68.82 2267.09   67.69 2279.15   69.17 2281.48    74.3 2287.05    77.7
  2293.8   78.03 2397.43   79.75 2762.03    80.3  2791.2   80.15 2805.52   79.23
 2865.55    79.9 3075.64    78.6 3105.65    79.2 3480.81   78.79  3523.4   79.53
#Mann= 3 , 0 , 0
       0     .15       0 2229.22     .04       0  2293.8     .08       0
#XS Ineff= 2 , 0
       0    2202            2433       0
Permanent Ineff=
       T       T
Bank Sta=2229.22,2293.8
XS Rating Curve= 0
Exp/Cntr=.5,.3

Type RM Length L Ch R = 1 ,10966   ,206.93,253.92,268.42
BEGIN DESCRIPTION:
10951  Copied surveyed cross-section 10970/XS1
END DESCRIPTION:
XS GIS Cut Line= 6
     3042969.374    13822416.949       3043060.6      13820193.7
      3043055.77      13820166.5      3043050.46      13820136.2
      3043046.29      13820112.6      3043083.01      13818894.9
#Sta/Elev= 30
       0   79.68   44.49   78.37  286.09   80.54  329.73   80.07  359.75   78.55
  949.45   78.95 1155.42   80.25 1530.74   80.25  1605.8   79.13 1641.65    80.3
 2031.01   80.26 2204.07    79.9 2233.18   77.68 2245.74    72.2 2247.67   68.82
 2262.09   67.69 2274.15   69.17 2276.48    74.3 2282.05    77.7 2305.32   78.78
 2327.58   78.53  2372.6   80.79 2627.72   81.47 2987.88   80.79 3077.92   79.06
 3137.95   80.74  3226.5   79.38 3393.07   79.91 3483.11   78.54 3525.73   79.28
#Mann= 3 , 0 , 0
       0     .15       0 2233.18     .04       0 2282.05     .08       0
#XS Ineff= 2 , 0
       0    2199            2399       0
Permanent Ineff=
       T       T
Bank Sta=2233.18,2282.05
XS Rating Curve= 0
Exp/Cntr=.3,.1

Type RM Length L Ch R = 1 ,10712   ,206,190.99,188.57
BEGIN DESCRIPTION:
10697  Surveyed cross-section
END DESCRIPTION:
XS GIS Cut Line= 4
     3043179.744    13822396.817     3043262.944    13820302.418
     3043298.788     13820210.02     3043327.237    13818899.488
#Sta/Elev= 30
       0   78.05   39.35   80.03   234.5   81.39  264.53   81.12  324.45   79.06
  834.97   79.41  925.05   77.81 1017.49   79.47 1150.22   79.71 1510.51   79.06
 1960.86   79.05 1975.87   79.63 2119.34    78.9 2150.79   67.08 2155.04   66.73
 2156.68   68.87 2179.83   79.64 2195.16   79.65 2207.68   78.14 2222.68   77.81
 2279.58   80.82 2477.74   81.39 2940.39   80.24  3122.9   80.97  3137.9   80.85
 3160.66    79.3 3424.99   79.95 3452.97   79.51 3482.98   78.04    3506   78.98
#Mann= 3 , 0 , 0
       0     .15       0 2119.34     .04       0 2179.83     .15       0
#XS Ineff= 2 , 0
       0    2090            2237       0
Permanent Ineff=
       T       T
Bank Sta=2119.34,2179.83
XS Rating Curve= 0
Exp/Cntr=.3,.1

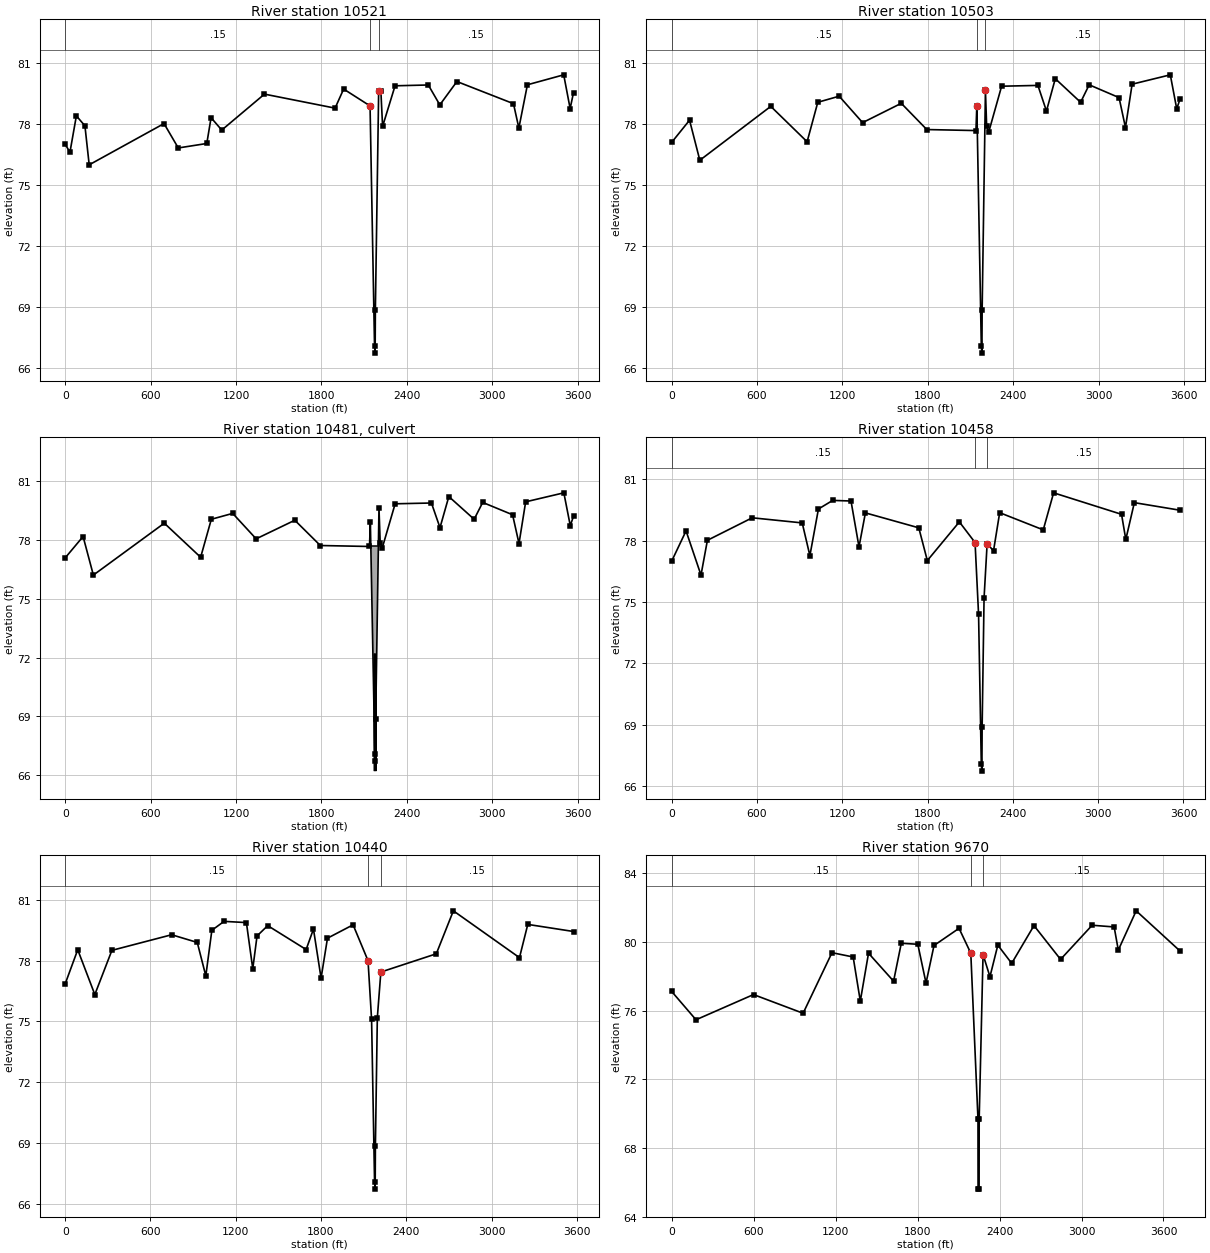
Type RM Length L Ch R = 1 ,10521   ,18,18,18.17
BEGIN DESCRIPTION:
10506  Copied surveyed cross-section 10697
END DESCRIPTION:
XS GIS Cut Line= 6
     3043362.561    13822465.791     3043468.913     13820353.47
     3043472.081     13820288.29     3043472.081     13820268.04
     3043473.982     13820250.95     3043512.281     13818898.64
#Sta/Elev= 30
       0   77.01   33.33   76.62   78.39   78.41  138.47   77.92   168.5      76
  694.17   78.03  794.25   76.83  994.55   77.05 1024.59   78.32 1099.68   77.71
 1399.62   79.48 1895.69   78.79 1955.77   79.73 2141.34    78.9 2172.79   67.08
 2177.04   66.73 2178.68   68.87 2201.83   79.64 2217.16   79.65 2229.42   77.89
 2316.97   79.89 2550.46   79.93 2631.39   78.95 2751.44    80.1 3148.76   79.01
 3186.61   77.81 3246.64   79.94 3501.74   80.43 3546.76   78.77 3570.63   79.56
#Mann= 3 , 0 , 0
       0     .15       0 2141.34     .04       0 2201.83     .15       0
#XS Ineff= 2 , 0
       0    2111            2261       0
Permanent Ineff=
       T       T
Bank Sta=2141.34,2201.83
XS Rating Curve= 0
Exp/Cntr=.5,.3

Type RM Length L Ch R = 1 ,10503   ,45.01,45,45.43
BEGIN DESCRIPTION:
10488  Copied surveyed cross-section 10697
END DESCRIPTION:
XS GIS Cut Line= 6
     3043380.472    13822467.979     3043486.896     13820354.27
     3043490.063     13820289.09     3043490.063     13820268.84
     3043491.964     13820251.76     3043530.263     13818899.44
#Sta/Elev= 30
       0   77.09  125.64   78.18  197.81   76.21  696.36   78.86  951.68   77.12
 1026.78   79.06 1176.97   79.36 1341.73   78.06 1613.42   79.01 1792.75   77.72
 2138.16   77.67 2144.34    78.9 2175.79   67.08 2180.04   66.73 2181.68   68.87
 2204.83   79.64 2213.38   77.87 2228.42   77.61 2318.45   79.85 2573.55   79.89
 2633.58   78.63 2695.65   80.22 2873.67   79.06  2933.7   79.92 3143.78   79.29
  3188.8   77.82 3235.58   79.95 3503.93   80.41 3548.95   78.74 3572.01   79.21
#Mann= 3 , 0 , 0
       0     .15       0 2144.34     .04       0 2204.83     .15       0
#XS Ineff= 2 , 0
       0    2111            2263       0
Permanent Ineff=
       T       T
Bank Sta=2144.34,2204.83
XS Rating Curve= 0
Exp/Cntr=.5,.3

Type RM Length L Ch R = 2 ,10481   ,,,
BEGIN DESCRIPTION:
10466  briar bayou - (2) 6' RCP
END DESCRIPTION:
Bridge Culvert--1,0,-1,-1, 0
Deck Dist Width WeirC Skew NumUp NumDn MinLoCord MaxHiCord MaxSubmerge Is_Ogee
1,43,2.6,0, 2, 2, 78.1, , .95, 0, 0,0,,
    2145 2207.24
    77.7    77.7
                
    2130    2220
    77.7    77.7
                
BR Coef=-1 , 0 , 0 ,, 0 ,,,.8,-1,,0,
WSPro=,,,, 1 ,,,, 0 ,,,, 0 ,,,,-1 ,-1 ,-1 , 0 , 0 , 0 , 0 , 0
Multiple Barrel Culv=1,6,,43,.012,.2,1,1,2,66.2,66.2, 2,Culvert #1  , 0 ,.05
 2172.92 2174.92 2182.92 2184.92
Culvert Bottom n=.012
BC Design=,, 0 ,, 0 ,,,,,,

Type RM Length L Ch R = 1 ,10458   ,18,18,18.17
BEGIN DESCRIPTION:
10443  Copied surveyed cross-section 10697
END DESCRIPTION:
XS GIS Cut Line= 6
     3043425.258     13822473.45     3043531.851     13820356.29
     3043535.019     13820291.11     3043535.019     13820270.86
     3043536.919     13820253.77     3043575.218     13818901.46
#Sta/Elev= 30
       0   76.99  101.08   78.47  206.21   76.31  251.27   78.01  566.67   79.11
  918.18   78.86  972.18   77.26 1032.26   79.54 1132.67   79.96 1261.36   79.93
 1317.62   77.69 1362.67   79.35 1738.15   78.62 1798.22   77.02 2023.51   78.91
 2133.98    77.9 2158.65   74.39 2177.79   67.08 2182.04   66.73 2183.68   68.87
 2197.27   75.19 2218.86   77.84  2263.9    77.5 2307.11   79.36 2613.56   78.52
 2686.52   80.33 3164.27   79.28 3194.28   78.05  3254.3   79.85 3575.47   79.48
#Mann= 3 , 0 , 0
       0     .15       0 2133.98     .04       0 2218.86     .15       0
#XS Ineff= 2 , 0
       0    2112            2268       0
Permanent Ineff=
       T       T
Bank Sta=2133.98,2218.86
XS Rating Curve= 0
Exp/Cntr=.5,.3

Type RM Length L Ch R = 1 ,10440   ,775.76,769.9,793.38
BEGIN DESCRIPTION:
10425  Copied surveyed cross-section 10697
END DESCRIPTION:
XS GIS Cut Line= 6
     3043443.168    13822475.638     3043549.833     13820357.09
     3043553.001     13820291.91     3043553.001     13820271.66
     3043554.902     13820254.58       3043593.2     13818902.26
#Sta/Elev= 30
       0   76.86   88.15   78.54   208.4   76.33  328.55   78.51  749.09   79.28
  929.31    78.9  989.39   77.25 1031.89    79.5 1117.68   79.94 1274.97   79.88
 1319.81    77.6 1349.85   79.22 1424.94   79.73 1695.28   78.55 1746.84   79.56
 1800.42   77.14 1845.47   79.11  2025.7   79.77 2130.82      78 2155.82    75.1
 2176.79   67.08 2181.04   66.73 2182.68   68.87 2196.27   75.19 2221.06   77.44
 2611.23   78.34 2731.28   80.46 3196.47   78.15 3254.91   79.79 3576.86   79.44
#Mann= 3 , 0 , 0
       0     .15       0 2130.82     .04       0 2221.06     .15       0
#XS Ineff= 2 , 0
       0    2113            2271       0
Permanent Ineff=
       T       T
Bank Sta=2130.82,2221.06
XS Rating Curve= 0
Exp/Cntr=.3,.1

Type RM Length L Ch R = 1 ,9670    ,473.49,478.13,479.38
BEGIN DESCRIPTION:
9656  Surveyed cross-section
END DESCRIPTION:
XS GIS Cut Line= 4
     3044175.946     13822565.15     3044322.186     13820380.48
     3044321.226    13820270.056     3044857.347    13818954.203
#Sta/Elev= 30
       0   77.12  178.05   75.47  598.99   76.94  962.09   75.85 1173.45   79.38
 1328.44   79.13 1380.73   76.56 1440.87   79.35 1624.34   77.72  1680.7   79.93
 1801.67   79.87 1861.81   77.61 1920.24    79.8 2103.41    80.8 2189.56   79.35
 2242.15   69.67 2242.74   65.63 2250.25    65.6 2250.91   69.69 2279.19   79.27
 2329.74   77.98 2387.32   79.82 2488.88   78.76 2652.01   80.96 2846.67   78.99
 3077.82   80.98 3238.94   80.88 3269.18   79.53 3400.05   81.82 3720.86   79.48
#Mann= 3 , 0 , 0
       0     .15       0 2189.56     .04       0 2279.19     .15       0
#XS Ineff= 2 , 0
       0    2077            2336       0
Permanent Ineff=
       T       T
Bank Sta=2189.56,2279.19
XS Rating Curve= 0
Exp/Cntr=.3,.1