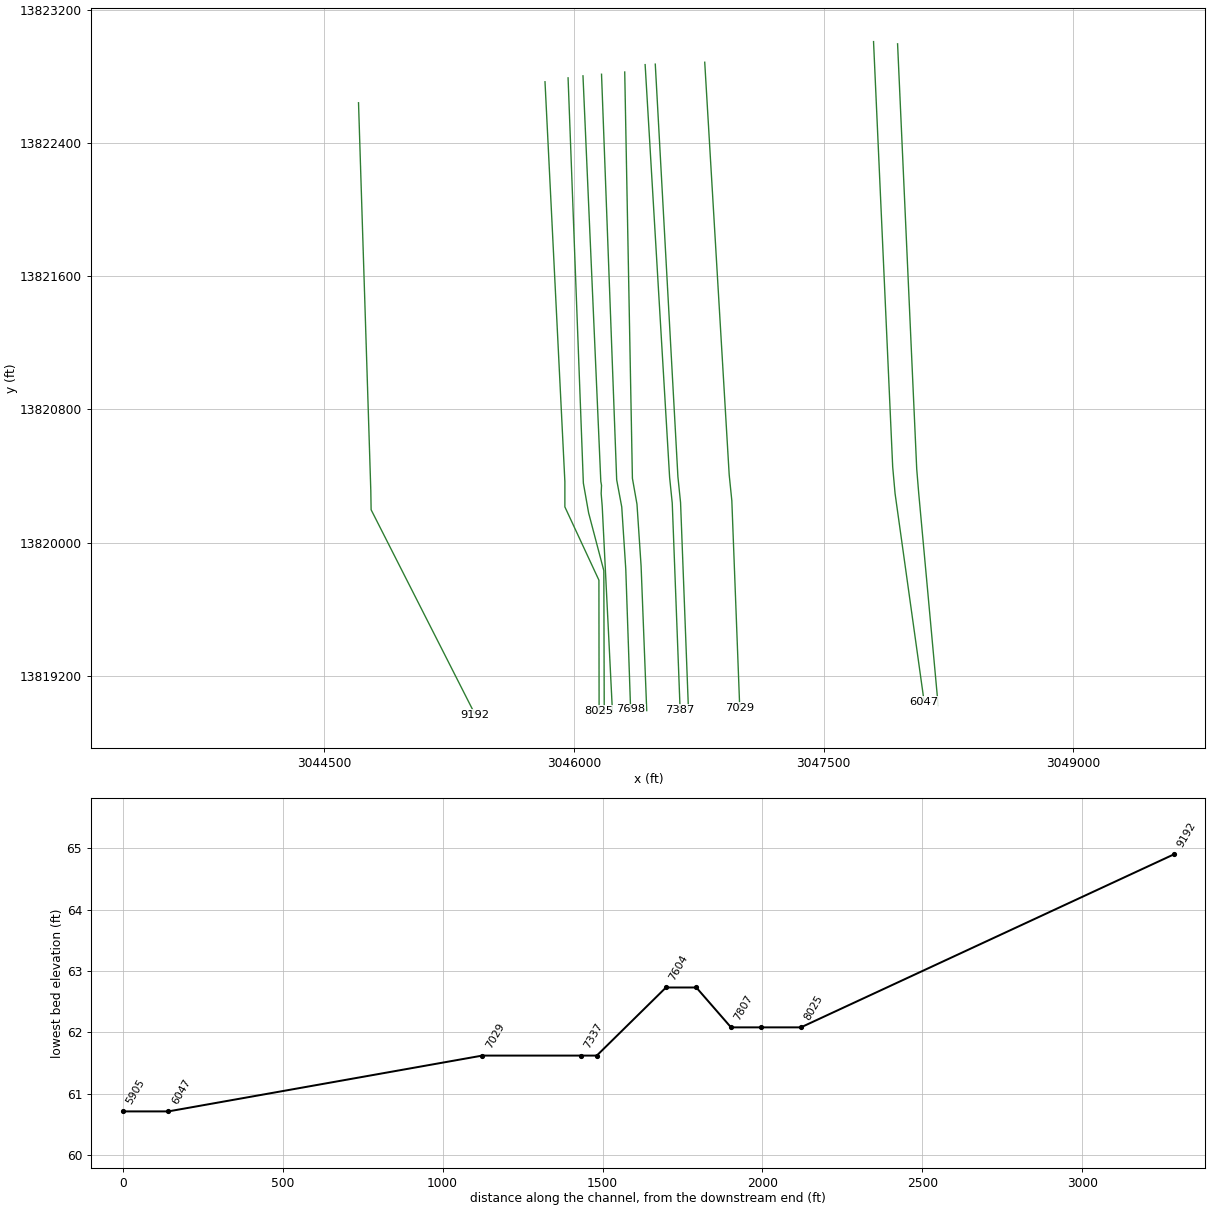
HEC-RAS study D126-00-00.prj: D126-00-00

--- D126-00-00.g02 (geometry) --- (continued)

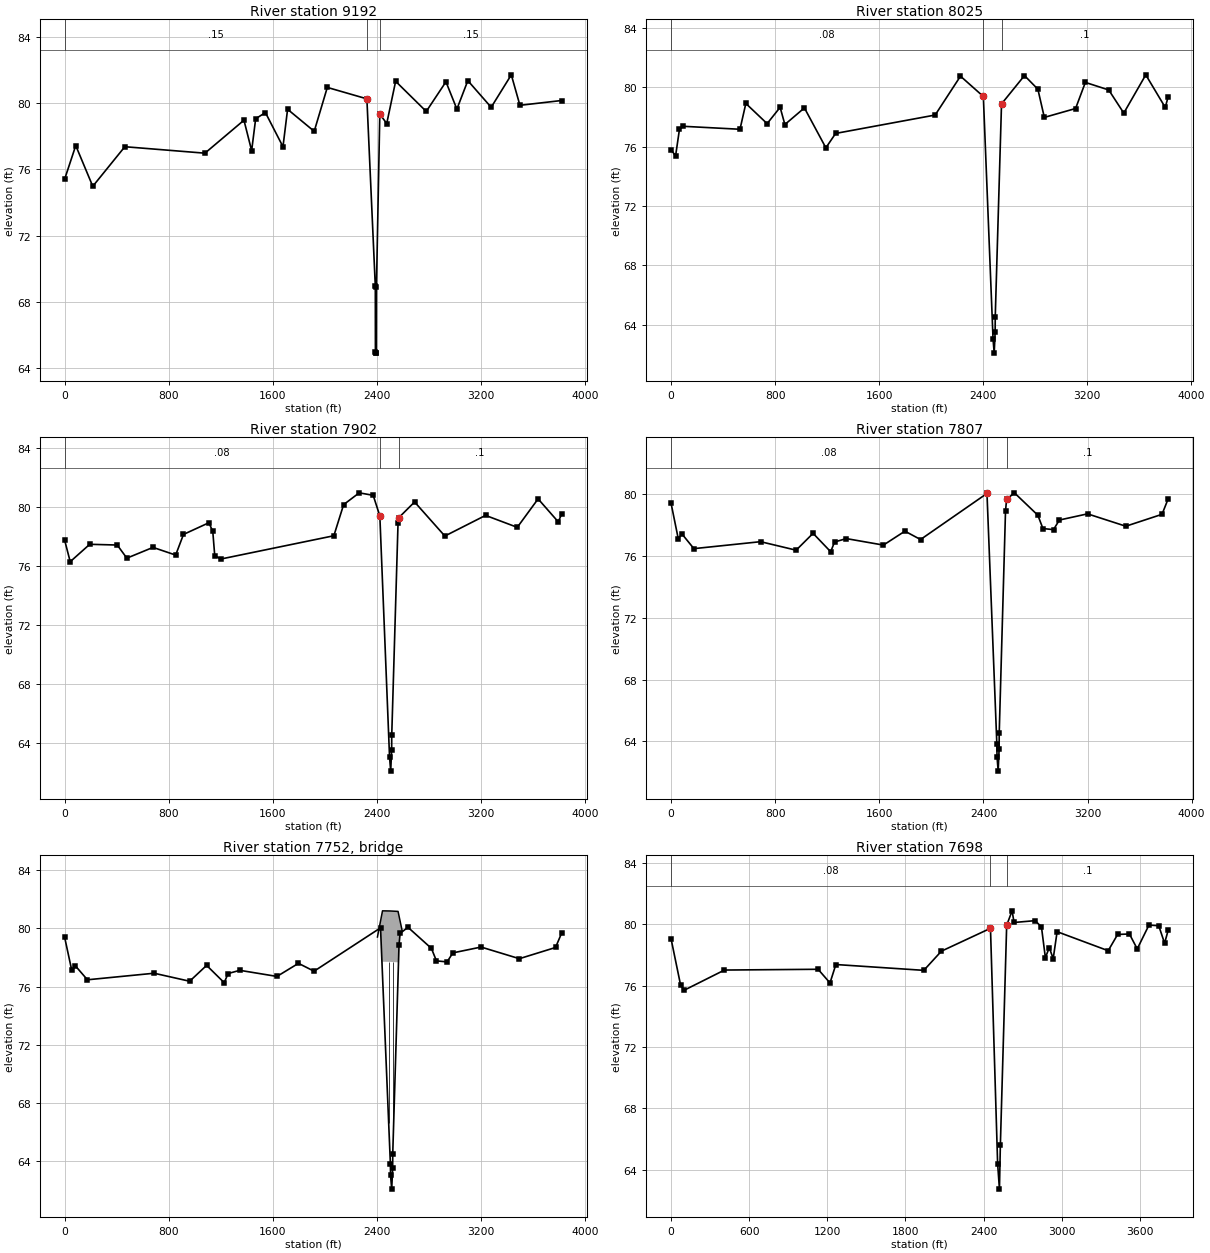
Type RM Length L Ch R = 1 ,9192    ,1169.6,1166.18,1156.12
BEGIN DESCRIPTION:
9177  Surveyed cross-section
END DESCRIPTION:
XS GIS Cut Line= 4
     3044707.843    13822640.889     3044781.571    13820313.672
     3044783.514    13820198.121     3045408.037     13818968.87
#Sta/Elev= 30
       0    75.4   85.38   77.43  216.31   74.97  462.88   77.36 1078.93   76.97
 1379.08   78.96 1438.23   77.12 1469.13   79.05 1544.16   79.42 1679.23   77.36
 1714.61   79.62 1919.35   78.29 2020.09   80.94 2324.55   80.25 2389.33   68.93
 2390.09   64.96 2393.63    64.9 2397.11   64.91 2398.03   68.89 2423.84   79.33
 2477.13   78.76  2545.6   81.31 2781.15   79.49 2932.57   81.28 3016.69   79.63
 3100.82   81.35 3280.41   79.74 3435.21    81.7 3501.44   79.86 3822.75   80.15
#Mann= 3 , 0 , 0
       0     .15       0 2324.55     .04       0 2423.84     .15       0
#XS Ineff= 2 , 0
       0    2115            2519       0
Permanent Ineff=
       T       T
Bank Sta=2324.55,2423.84
XS Rating Curve= 0
Exp/Cntr=.3,.1

Type RM Length L Ch R = 1 ,8025    ,111,123.7,120.7
BEGIN DESCRIPTION:
8011  Surveyed cross-section
END DESCRIPTION:
XS GIS Cut Line= 5
     3045827.383     13822766.88     3045946.688    13820367.143
     3045946.688    13820215.371     3046151.047    13819775.704
     3046152.192    13818990.225
#Sta/Elev= 30
       0   75.79   34.42   75.37   64.46   77.18    94.5   77.37  530.03   77.17
  575.09   78.91  738.73   77.55  838.88   78.65  875.46   77.49 1025.65   78.61
 1190.85   75.92 1265.94   76.89 2031.89   78.13 2226.68   80.75  2402.7   79.38
 2477.37   63.02 2486.13   62.08 2493.45   63.51 2494.17   64.52  2542.5   78.88
  2719.1   80.79  2822.3   79.87 2871.92   77.97 3112.52   78.57 3187.52   80.33
 3367.52   79.82 3483.32   78.26 3652.52   80.84 3802.52   78.64 3824.79   79.37
#Mann= 3 , 0 , 0
       0     .08       0  2402.7     .04       0  2542.5      .1       0
#XS Ineff= 2 , 0
       0    1901            2604       0
Permanent Ineff=
       T       T
Bank Sta=2402.7,2542.5
XS Rating Curve= 0
Exp/Cntr=.3,.1

Type RM Length L Ch R = 1 ,7902    ,104.85,94.86,78.97
BEGIN DESCRIPTION:
7888  Copied surveyed cross-section 8011/XS4
END DESCRIPTION:
XS GIS Cut Line= 6
     3045965.886    13822790.251     3046057.638     13820358.41
     3046063.364     13820326.12     3046089.264      13820179.2
     3046180.524      13819832.7     3046182.999    13818986.089
#Sta/Elev= 30
       0   77.74   42.78   76.28  192.89   77.46  404.41   77.41  478.09   76.52
  679.24   77.25  853.36   76.73   913.4   78.13 1108.54   78.92 1138.56   78.34
 1153.57    76.7 1199.98   76.46 2069.22   78.04 2144.28   80.15 2264.36   80.95
 2371.63   80.78  2422.7   79.38 2497.37   63.02 2506.13   62.08 2513.45   63.51
 2514.17   64.52  2562.5   78.88  2566.5   79.25  2689.7   80.33 2922.37   78.02
 3235.28   79.42 3479.07   78.61  3639.1   80.54 3794.07   78.98 3820.48   79.52
#Mann= 3 , 0 , 0
       0     .08       0  2422.7     .04       0  2566.5      .1       0
#XS Ineff= 2 , 0
       0    1955            2611       0
Permanent Ineff=
       T       T
Bank Sta=2422.7,2566.5
XS Rating Curve= 0
Exp/Cntr=.5,.3

Type RM Length L Ch R = 1 ,7807    ,95.88,108.49,118.85
BEGIN DESCRIPTION:
7793  Copied surveyed cross-section 8011/XS3
END DESCRIPTION:
XS GIS Cut Line= 6
      3046055.42    13822802.345     3046162.463     13820368.63
     3046166.762      13820344.4     3046164.532     13820295.79
     3046170.808     13820220.38     3046232.208    13818987.582
#Sta/Elev= 30
       0   79.39    54.9   77.11   83.34   77.42  175.01   76.47  687.39   76.92
  960.64   76.37  1090.9   77.46 1226.03   76.27 1256.06    76.9 1346.15   77.12
 1631.42    76.7 1796.58    77.6  1916.7   77.06 2427.19   80.04 2502.96   63.84
 2504.37   63.02 2513.13   62.08 2520.45   63.51 2521.17   64.52  2569.5   78.88
 2577.89   79.66 2637.94   80.08  2818.2   78.63 2856.94   77.77 2938.37    77.7
 2983.42   78.32 3199.95   78.72 3494.06   77.92 3772.07   78.69 3819.39   79.69
#Mann= 3 , 0 , 0
       0     .08       0 2427.19     .04       0 2577.89      .1       0
#XS Ineff= 2 , 0
       0    2001            2626       0
Permanent Ineff=
       T       T
Bank Sta=2427.19,2577.89
XS Rating Curve= 0
Exp/Cntr=.5,.3

Type RM Length L Ch R = 3 ,7752    ,,,
BEGIN DESCRIPTION:
7738  bridge at dairy ashford
END DESCRIPTION:
Bridge Culvert--1,0,-1,-1, 0
Deck Dist Width WeirC Skew NumUp NumDn MinLoCord MaxHiCord MaxSubmerge Is_Ogee
16.745,75,2.6,0, 5, 7, 80.6, , .95, 0, 0,0,,
 2403.56 2442.47 2502.22 2561.97 2593.12
   79.41   81.21    81.2   81.17   79.86
           77.71    77.7   77.67
 2416.56 2455.47 2463.74 2515.22  2566.7 2574.97 2606.12
   79.41   81.21   81.21    81.2   81.17   81.17   79.86
                   77.71    77.7   77.67
Pier Skew, UpSta & Num, DnSta & Num=  ,2489.8, 2 ,2498.48, 2 , 0 , 0 , 0 ,,
     2.5     2.5
       0     100
     2.5     2.5
       0     100
Pier Skew, UpSta & Num, DnSta & Num=  ,2524.64, 2 ,2533.32, 2 , 0 , 0 , 0 ,,
     2.5     2.5
       0     100
     2.5     2.5
       0     100
BR Coef=-1 , 1 , 1 ,1.25, 0 ,,,.8,-1,2,0,
WSPro=,,,, 1 ,,,, 0 ,,,, 0 ,,,,-1 ,-1 ,-1 , 0 , 0 , 0 , 0 , 0
BC Design=,, 0 ,, 0 ,,,,,,

Type RM Length L Ch R = 1 ,7698    ,95.33,94.82,92.49
BEGIN DESCRIPTION:
7684  Surveyed cross-section/XS2
END DESCRIPTION:
XS GIS Cut Line= 5
     3046166.731     13822812.02     3046257.766    13820377.829
     3046288.119    13820215.001     3046312.307    13819841.868
     3046341.345    13819000.105
#Sta/Elev= 30
       0   79.03   72.62   76.04  101.56    75.7  409.81   77.01 1128.89   77.06
 1220.37   76.17  1265.4   77.37 1940.88   76.99 2075.97   78.24 2452.98   79.73
 2507.85   64.39 2521.81   62.73 2528.87   65.59 2577.37   79.93 2619.06   80.87
 2634.09   80.11 2796.22   80.23 2844.54   79.82  2874.6   77.82 2904.66   78.47
 2934.72   77.75 2964.79   79.51 3357.07   78.27 3429.61   79.33 3520.13   79.36
 3580.17   78.39 3670.22   79.94 3745.27    79.9 3790.29   78.76 3817.71    79.6
#Mann= 3 , 0 , 0
       0     .08       0 2452.98     .04       0 2577.37      .1       0
#XS Ineff= 2 , 0
       0    2041            2662       0
Permanent Ineff=
       T       T
Bank Sta=2452.98,2577.37
XS Rating Curve= 0
Exp/Cntr=.1,.3

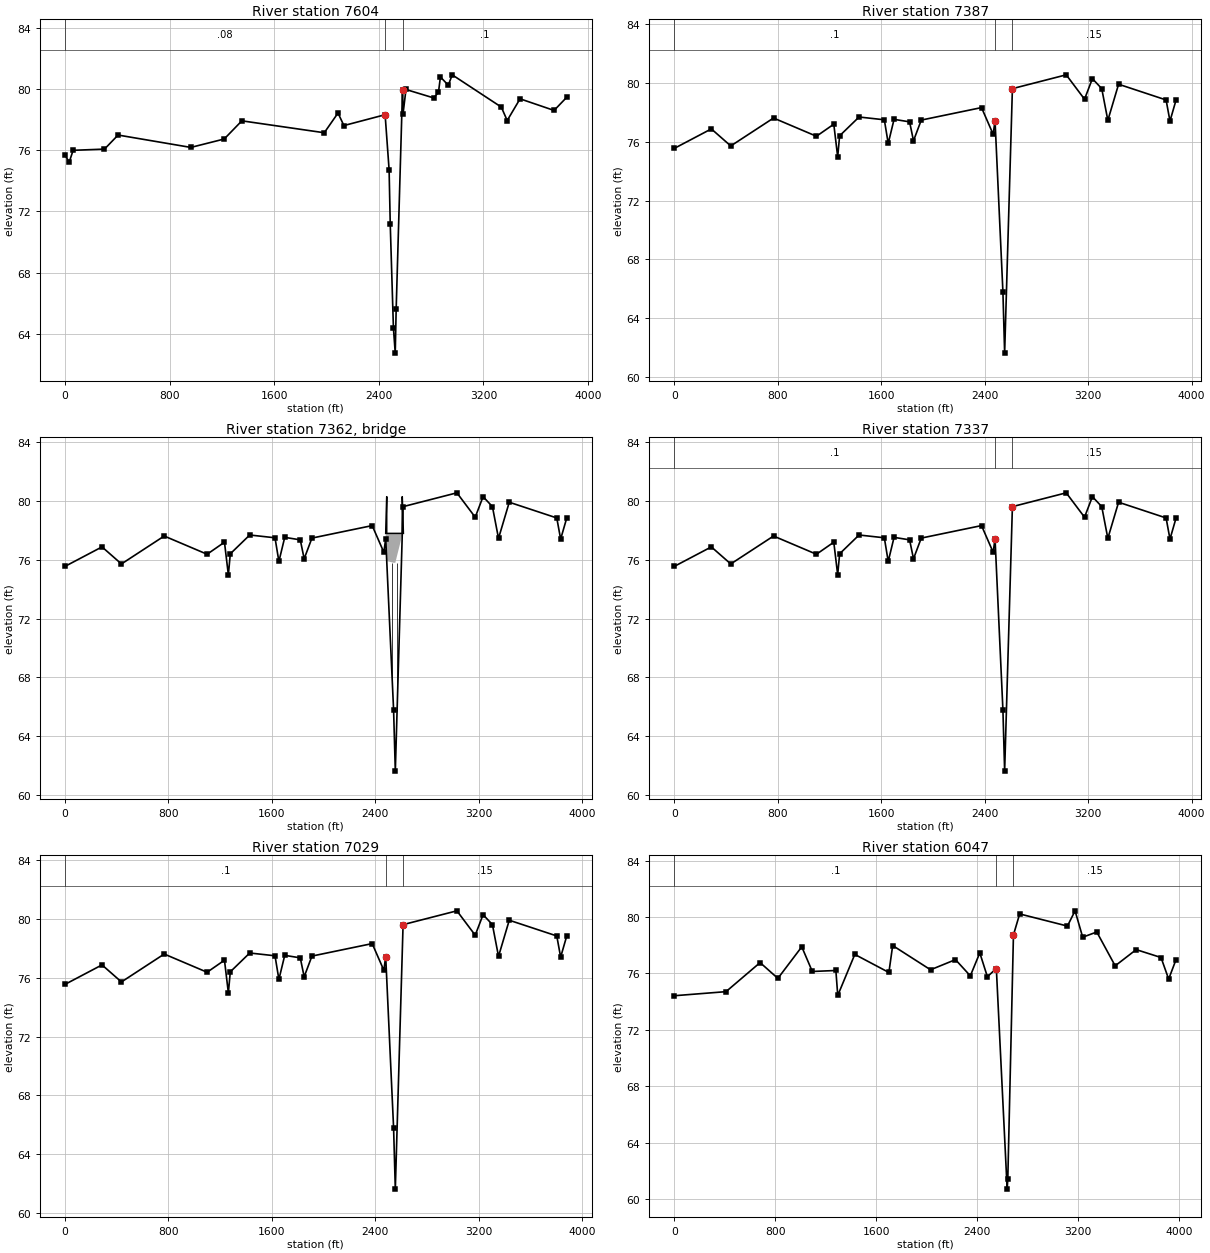
Type RM Length L Ch R = 1 ,7604    ,221.84,216.32,210.14
BEGIN DESCRIPTION:
7589  Copied surveyed cross-section 7684/XS1
END DESCRIPTION:
XS GIS Cut Line= 6
     3046306.018    13822825.348     3046352.147     13820387.13
     3046367.038     13820302.62     3046379.598     13820231.47
      3046404.26    13819861.219     3046438.138    13818992.848
#Sta/Elev= 30
       0   75.71   32.85   75.22   62.86      76   302.9   76.08  406.71      77
  963.02   76.19 1218.07   76.74 1353.09   77.93  1983.2   77.15 2088.22   78.44
 2133.23   77.62 2448.44   78.33  2478.9   74.73 2487.65   71.16 2511.85   64.39
 2525.81   62.73 2532.87   65.59 2581.37   79.93 2585.52   78.39 2607.87   79.98
 2819.29   79.43 2856.26   79.79 2871.29    80.8 2931.43   80.26 2961.49   80.94
 3336.79   78.83 3381.82   77.95 3480.16   79.37 3740.22   78.61 3836.82   79.47
#Mann= 3 , 0 , 0
       0     .08       0 2448.44     .04       0 2581.37      .1       0
#XS Ineff= 2 , 0
       0    2068            2679       0
Permanent Ineff=
       T       T
Bank Sta=2448.44,2581.37
XS Rating Curve= 0
Exp/Cntr=.5,.3

Type RM Length L Ch R = 1 ,7387    ,50.01,50.06,50
BEGIN DESCRIPTION:
7372  Surveyed cross-section
END DESCRIPTION:
XS GIS Cut Line= 4
       3046428.5      13822869.6       3046575.5      13820392.8
       3046591.3      13820237.9       3046638.6      13818997.4
#Sta/Elev= 30
       0   75.55  287.02   76.88  437.28   75.72  767.86   77.62 1099.53   76.38
 1233.68    77.2 1263.73   74.98 1278.76   76.41 1429.02   77.69 1624.37    77.5
 1654.42   75.89  1699.5   77.53 1819.71   77.36 1849.76   76.07 1909.87   77.48
 2375.69   78.33 2465.84   76.51 2480.09   77.45 2541.11   65.78 2554.38   61.62
 2614.41   79.62  3030.4   80.56 3172.06    78.9 3232.82    80.3 3305.11   79.62
  3352.2   77.46 3435.24   79.92 3802.52   78.85 3832.55   77.41 3879.32   78.84
#Mann= 3 , 0 , 0
       0      .1       0 2480.09     .04       0 2614.41     .15       0
#XS Ineff= 2 , 0
       0    2119            2653       0
Permanent Ineff=
       T       T
Bank Sta=2480.09,2614.41
XS Rating Curve= 0
Exp/Cntr=.5,.3

Type RM Length L Ch R = 3 ,7362    ,,,
BEGIN DESCRIPTION:
7347  West School Bridge
END DESCRIPTION:
Bridge Culvert--1,0,-1,-1, 0
Deck Dist Width WeirC Skew NumUp NumDn MinLoCord MaxHiCord MaxSubmerge Is_Ogee
7,36,2.6,0, 6, 6, , , .95, 0, 0,0,,
    2480    2488  2488.1    2608  2608.1    2617
    77.8    80.3    77.8    77.8    80.3    77.8
    75.8    75.8    75.8    75.8    75.8    75.8
    2480    2488  2488.1    2608  2608.1    2617
    77.8    80.3    77.8    77.8    80.3    77.8
    75.8    75.8    75.8    75.8    75.8    75.8
Pier Skew, UpSta & Num, DnSta & Num=  ,2530, 2 ,2530, 2 , 0 , 0 , 0 ,,
     2.5     2.5
       0      80
     2.5     2.5
       0      80
Pier Skew, UpSta & Num, DnSta & Num=  ,2568, 2 ,2568, 2 , 0 , 0 , 0 ,,
     2.5     2.5
       0      80
     2.5     2.5
       0      80
BR Coef=-1 , 1 , 1 ,1.25, 0 ,,,.8,-1,2,0,
WSPro=,,,, 1 ,,,, 0 ,,,, 0 ,,,,-1 ,-1 ,-1 , 0 , 0 , 0 , 0 , 0
BC Design=,, 0 ,, 0 ,,,,,,

Type RM Length L Ch R = 1 ,7337    ,308.04,307.82,308.08
BEGIN DESCRIPTION:
7322  Surveyed cross-section
END DESCRIPTION:
XS GIS Cut Line= 4
       3046489.4      13822872.6       3046625.3      13820396.8
       3046641.2      13820241.4       3046688.6      13818999.3
#Sta/Elev= 30
       0   75.55  287.02   76.88  437.28   75.72  767.86   77.62 1099.53   76.38
 1233.68    77.2 1263.73   74.98 1278.76   76.41 1429.02   77.69 1624.37    77.5
 1654.42   75.89  1699.5   77.53 1819.71   77.36 1849.76   76.07 1909.87   77.48
 2375.69   78.33 2465.84   76.51 2480.09   77.45 2541.11   65.78 2554.38   61.62
 2614.41   79.62  3030.4   80.56 3172.06    78.9 3232.82    80.3 3305.11   79.62
  3352.2   77.46 3435.24   79.92 3802.52   78.85 3832.55   77.41 3879.32   78.84
#Mann= 3 , 0 , 0
       0      .1       0 2480.09     .04       0 2614.41     .15       0
#XS Ineff= 2 , 0
       0    2119            2653       0
Permanent Ineff=
       T       T
Bank Sta=2480.09,2614.41
XS Rating Curve= 0
Exp/Cntr=.5,.3

Type RM Length L Ch R = 1 ,7029    ,983.27,981.87,987.95
BEGIN DESCRIPTION:
7015  Surveyed cross-section
END DESCRIPTION:
XS GIS Cut Line= 4
       3046786.3    13822884.016     3046933.177    13820408.274
     3046949.022    13820252.859     3046996.469    13819010.758
#Sta/Elev= 30
       0   75.55  287.02   76.88  437.28   75.72  767.86   77.62 1099.53   76.38
 1233.68    77.2 1263.73   74.98 1278.76   76.41 1429.02   77.69 1624.37    77.5
 1654.42   75.89  1699.5   77.53 1819.71   77.36 1849.76   76.07 1909.87   77.48
 2375.69   78.33 2465.84   76.51 2480.09   77.45 2541.11   65.78 2554.38   61.62
 2614.41   79.62  3030.4   80.56 3172.06    78.9 3232.82    80.3 3305.11   79.62
  3352.2   77.46 3435.24   79.92 3802.52   78.85 3832.55   77.41 3879.32   78.84
#Mann= 3 , 0 , 0
       0      .1       0 2480.09     .04       0 2614.41     .15       0
#XS Ineff= 2 , 0
       0    2119            2653       0
Permanent Ineff=
       T       T
Bank Sta=2480.09,2614.41
XS Rating Curve= 0
Exp/Cntr=.3,.1

Type RM Length L Ch R = 1 ,6047    ,143.59,142.19,138.51
BEGIN DESCRIPTION:
6033  Surveyed cross-section
END DESCRIPTION:
XS GIS Cut Line= 4
     3047799.773    13823007.815     3047914.699     13820456.49
     3047929.004    13820296.147     3048103.785    13819044.666
#Sta/Elev= 30
       0   74.42  410.73   74.71     681   76.77  821.89   75.65 1011.34   77.89
 1094.88   76.14 1281.67   76.21 1296.63   74.44 1431.77   77.35 1702.04   76.07
 1732.07   77.98 2032.37   76.26 2229.95   76.98 2347.69   75.83 2422.77   77.46
 2482.83   75.77 2553.91   76.35  2639.7   60.71 2644.88   61.45 2689.57   78.73
 2738.77   80.22 3117.41   79.36 3177.99   80.44 3238.57   78.57 3350.26   78.94
 3496.05   76.54 3662.65   77.69 3859.54   77.13 3920.12    75.6 3978.52   76.98
#Mann= 3 , 0 , 0
       0      .1       0 2553.91     .04       0 2689.57     .15       0
#XS Ineff= 2 , 0
       0    2213            2733       0
Permanent Ineff=
       T       T
Bank Sta=2553.91,2689.57
XS Rating Curve= 0
Exp/Cntr=.5,.3

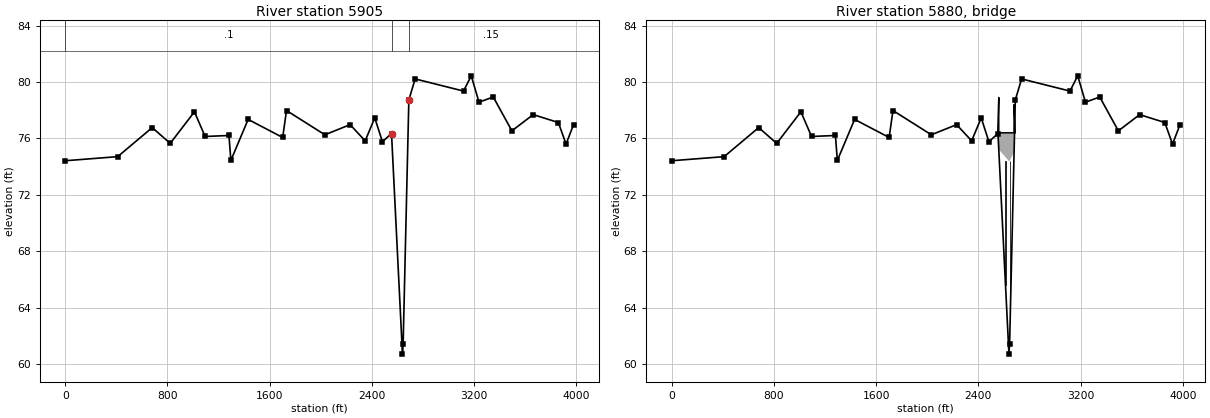
Type RM Length L Ch R = 1 ,5905    ,50,50.02,50.1
BEGIN DESCRIPTION:
5891  Surveyed cross-section
END DESCRIPTION:
XS GIS Cut Line= 4
       3047944.1      13822994.5        3048059.      13820443.2
       3048070.8      13820299.7       3048187.9      13819022.5
#Sta/Elev= 30
       0   74.42  410.73   74.71     681   76.77  821.89   75.65 1011.34   77.89
 1094.88   76.14 1281.67   76.21 1296.63   74.44 1431.77   77.35 1702.04   76.07
 1732.07   77.98 2032.37   76.26 2229.95   76.98 2347.69   75.83 2422.77   77.46
 2482.83   75.77 2553.91   76.35  2639.7   60.71 2644.88   61.45 2689.57   78.73
 2738.77   80.22 3117.41   79.36 3177.99   80.44 3238.57   78.57 3350.26   78.94
 3496.05   76.54 3662.65   77.69 3859.54   77.13 3920.12    75.6 3978.52   76.98
#Mann= 3 , 0 , 0
       0      .1       0 2553.91     .04       0 2689.57     .15       0
#XS Ineff= 2 , 0
       0    2213            2733       0
Permanent Ineff=
       T       T
Bank Sta=2553.91,2689.57
XS Rating Curve= 0
Exp/Cntr=.5,.3

Type RM Length L Ch R = 3 ,5880    ,,,
BEGIN DESCRIPTION:
5866  East School Bridge
END DESCRIPTION:
Bridge Culvert--1,0,-1,-1, 0
Deck Dist Width WeirC Skew NumUp NumDn MinLoCord MaxHiCord MaxSubmerge Is_Ogee
7,36,2.6,0, 6, 6, , , .95, 0, 0,0,,
    2552    2560  2560.1    2680  2680.1    2689
    76.4    78.9    76.4    76.4    78.4    76.4
    74.4    74.4    74.4    74.4    74.4    74.4
    2552    2560  2560.1    2680  2680.1    2689
    76.4    78.9    76.4    76.4    78.4    76.4
    74.4    74.4    74.4    74.4    74.4    74.4
Pier Skew, UpSta & Num, DnSta & Num=  ,2613, 2 ,2613, 2 , 0 , 0 , 0 ,,
     2.5     2.5
       0      80
     2.5     2.5
       0      80
Pier Skew, UpSta & Num, DnSta & Num=  ,2650, 2 ,2650, 2 , 0 , 0 , 0 ,,
     2.5     2.5
       0      80
     2.5     2.5
       0      80
BR Coef=-1 , 1 , 1 ,1.25, 0 ,,,.8,-1,2,0,
WSPro=,,,, 1 ,,,, 0 ,,,, 0 ,,,,-1 ,-1 ,-1 , 0 , 0 , 0 , 0 , 0
BC Design=,, 0 ,, 0 ,,,,,,