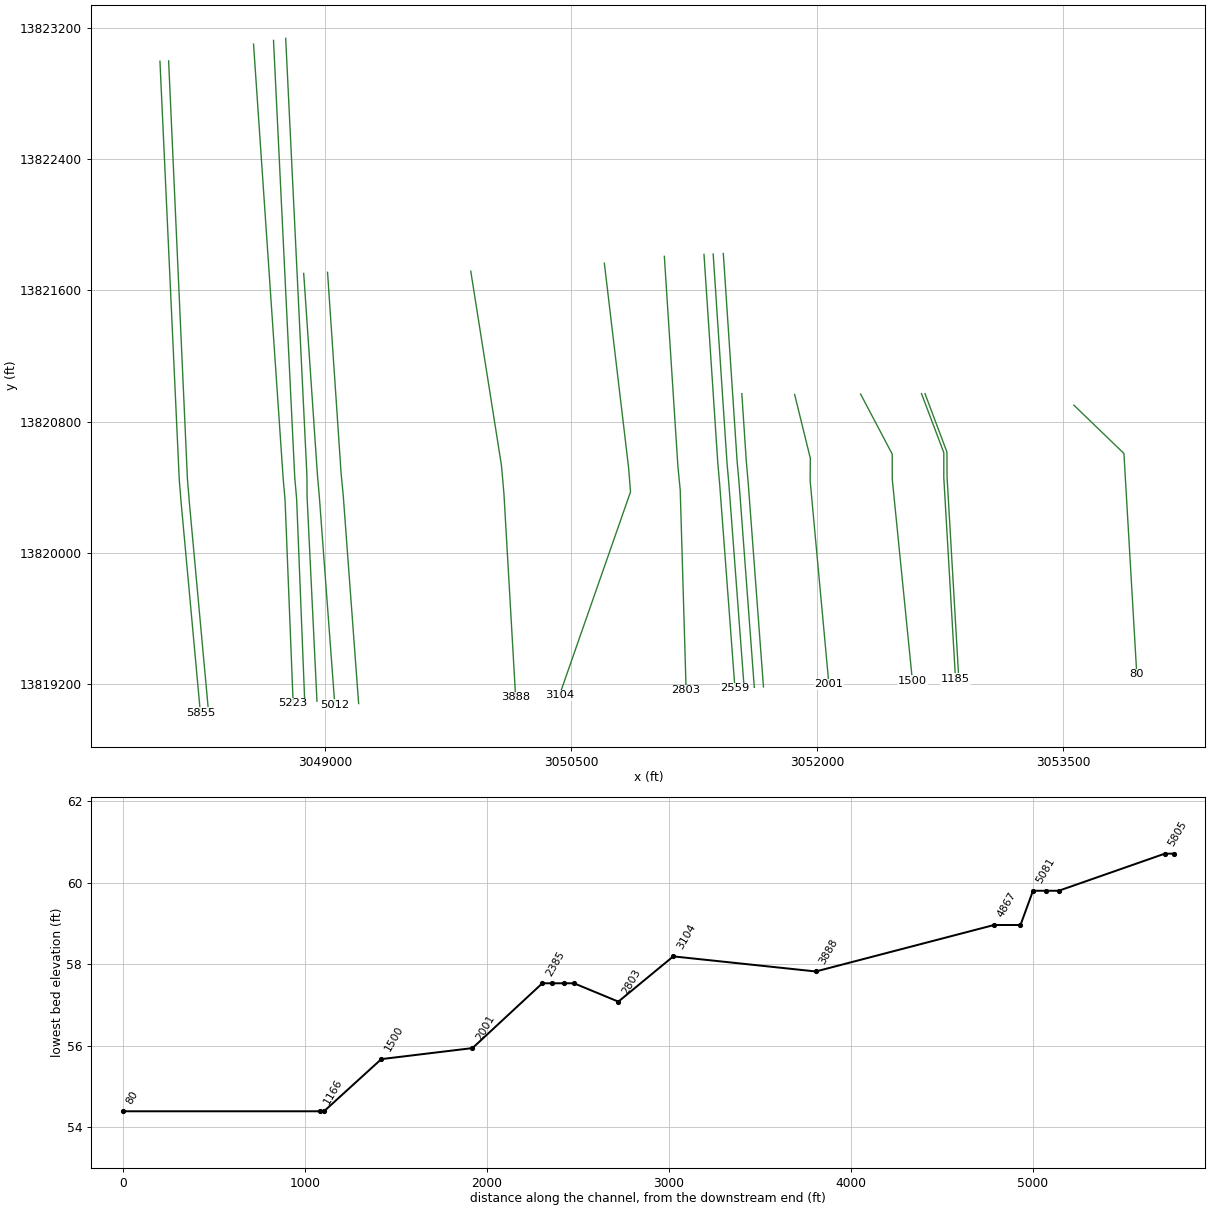
HEC-RAS study D126-00-00.prj: D126-00-00

--- D126-00-00.g02 (geometry) --- (continued)

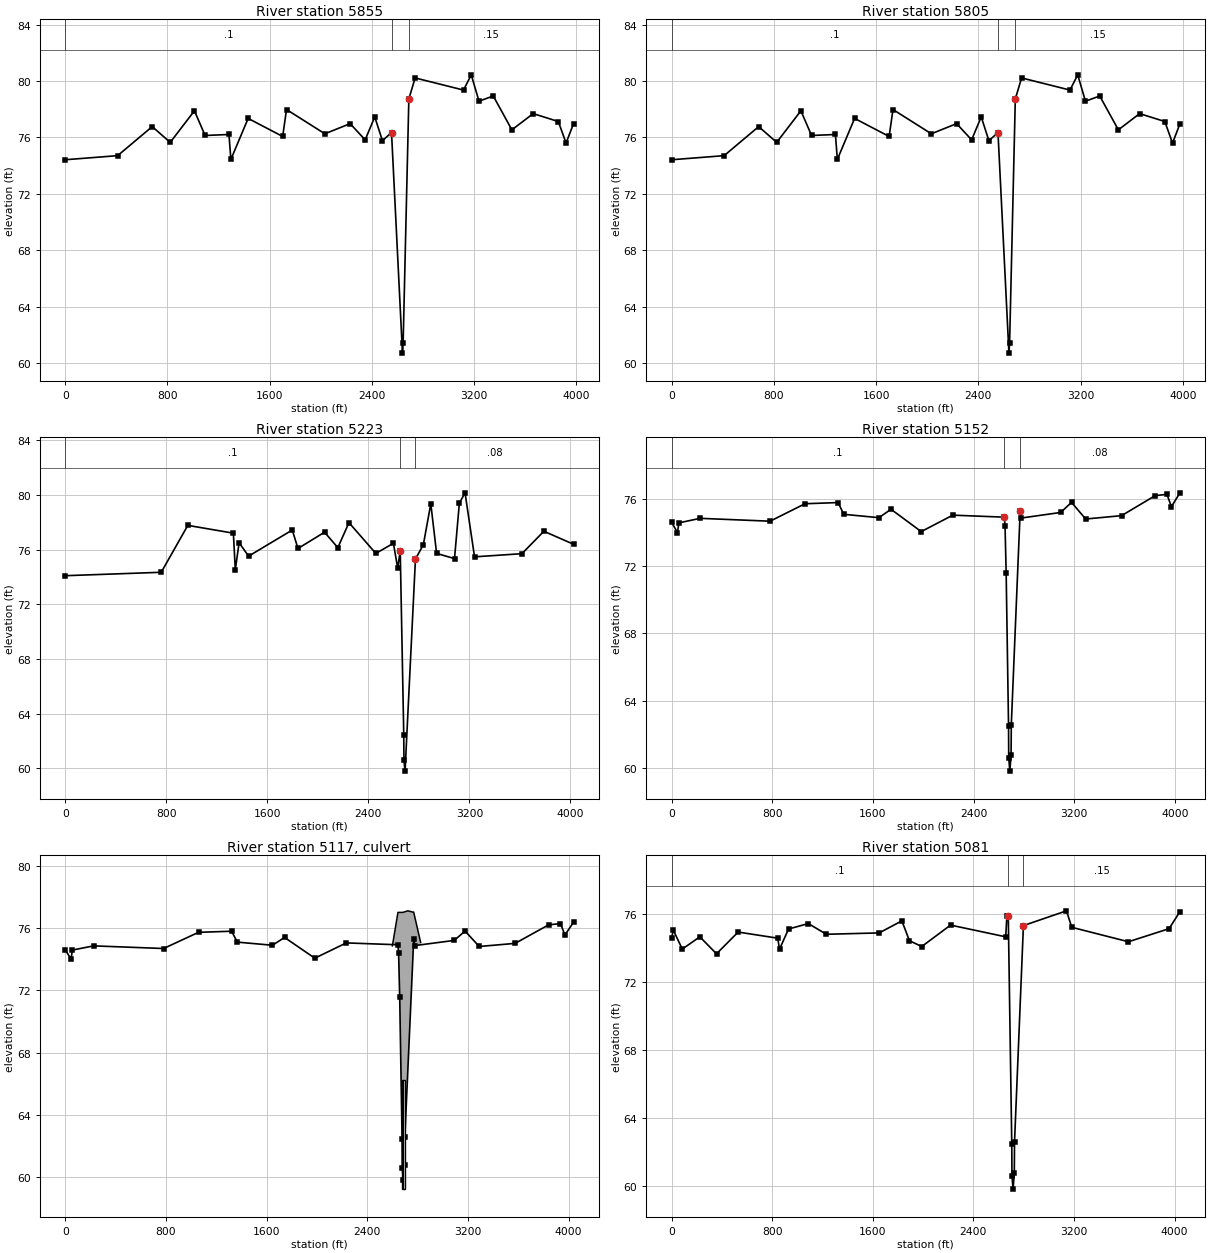
Type RM Length L Ch R = 1 ,5855    ,50,50.02,50.1
BEGIN DESCRIPTION:
5841  Surveyed cross-section
END DESCRIPTION:
XS GIS Cut Line= 4
       3047991.1      13822996.8       3048108.9      13820446.4
       3048120.6      13820304.1       3048237.7      13819027.1
#Sta/Elev= 30
       0   74.42  410.73   74.71     681   76.77  821.89   75.65 1011.34   77.89
 1094.88   76.14 1281.67   76.21 1296.63   74.44 1431.77   77.35 1702.04   76.07
 1732.07   77.98 2032.37   76.26 2229.95   76.98 2347.69   75.83 2422.77   77.46
 2482.83   75.77 2553.91   76.35  2639.7   60.71 2644.88   61.45 2689.57   78.73
 2738.77   80.22 3117.41   79.36 3177.99   80.44 3238.57   78.57 3350.26   78.94
 3496.05   76.54 3662.65   77.69 3859.54   77.13 3920.12    75.6 3978.52   76.98
#Mann= 3 , 0 , 0
       0      .1       0 2553.91     .04       0 2689.57     .15       0
#XS Ineff= 2 , 0
       0    2213            2733       0
Permanent Ineff=
       T       T
Bank Sta=2553.91,2689.57
XS Rating Curve= 0
Exp/Cntr=.5,.3

Type RM Length L Ch R = 1 ,5805    ,581.64,582.61,579.88
BEGIN DESCRIPTION:
5791  Surveyed cross-section
END DESCRIPTION:
XS GIS Cut Line= 4
        3048044.       13822999.       3048158.8      13820449.6
       3048170.4      13820308.4       3048287.5      13819031.7
#Sta/Elev= 30
       0   74.42  410.73   74.71     681   76.77  821.89   75.65 1011.34   77.89
 1094.88   76.14 1281.67   76.21 1296.63   74.44 1431.77   77.35 1702.04   76.07
 1732.07   77.98 2032.37   76.26 2229.95   76.98 2347.69   75.83 2422.77   77.46
 2482.83   75.77 2553.91   76.35  2639.7   60.71 2644.88   61.45 2689.57   78.73
 2738.77   80.22 3117.41   79.36 3177.99   80.44 3238.57   78.57 3350.26   78.94
 3496.05   76.54 3662.65   77.69 3859.54   77.13 3920.12    75.6 3978.52   76.98
#Mann= 3 , 0 , 0
       0      .1       0 2553.91     .04       0 2689.57     .15       0
#XS Ineff= 2 , 0
       0    2213            2733       0
Permanent Ineff=
       T       T
Bank Sta=2553.91,2689.57
XS Rating Curve= 0
Exp/Cntr=.3,.1

Type RM Length L Ch R = 1 ,5223    ,72.22,70.98,70.81
BEGIN DESCRIPTION:
5209  Copied surveyed cross-section 5067/XS4
END DESCRIPTION:
XS GIS Cut Line= 6
     3048561.834    13823100.904      3048742.44     13820455.09
     3048743.395     13820444.06     3048748.205     13820389.34
     3048754.026     13820322.68     3048803.383    13819084.386
#Sta/Elev= 30
       0   74.09  760.17   74.34  970.66   77.77 1331.32    77.2 1346.53   74.53
  1376.6    76.5 1451.77   75.52 1797.58   77.43 1842.68   76.08 2053.17   77.27
 2158.42   76.14 2246.31   77.97 2459.11   75.72 2598.16   76.46    2632   74.65
 2652.26    75.9 2680.15   62.47 2681.59   60.58 2690.42    59.8 2772.73   75.31
 2835.11   76.35 2894.27   79.35 2940.19   75.72 3081.95   75.34 3120.33    79.4
 3165.37   80.15 3240.43   75.47 3615.73    75.7 3789.34   77.34 4024.17   76.39
#Mann= 3 , 0 , 0
       0      .1       0 2652.26     .04       0 2772.73     .08       0
#XS Ineff= 2 , 0
       0    2464            2914       0
Permanent Ineff=
       T       T
Bank Sta=2652.26,2772.73
XS Rating Curve= 0
Exp/Cntr=.5,.3

Type RM Length L Ch R = 1 ,5152    ,74.73,70.51,64.89
BEGIN DESCRIPTION:
5138  Copied surveyed cross-section 5067/XS3
END DESCRIPTION:
XS GIS Cut Line= 6
     3048683.614    13823123.536     3048813.029    13820462.029
     3048813.917    13820451.769     3048818.722    13820397.089
     3048824.592    13820329.889      3048874.18    13819088.471
#Sta/Elev= 30
       0   74.62   46.09   74.01   57.21   74.59   226.3   74.86  781.96   74.69
 1059.71   75.73  1322.6    75.8 1367.65    75.1 1646.88    74.9 1743.09    75.4
 1983.38   74.07 2234.06   75.05 2644.16   74.93 2649.37   74.38 2658.24   71.58
 2677.15   62.47 2678.59   60.58 2687.42    59.8 2697.26   60.76 2699.03   62.57
 2769.73   75.31 2779.62   74.88  3091.1   75.21 3177.71   75.81 3290.08   74.82
  3575.3   75.02 3841.74   76.21 3935.59   76.29 3971.66   75.56  4039.7   76.38
#Mann= 3 , 0 , 0
       0      .1       0 2644.16     .04       0 2769.73     .08       0
#XS Ineff= 2 , 0
       0    2476            2888       0
Permanent Ineff=
       T       T
Bank Sta=2644.16,2769.73
XS Rating Curve= 0
Exp/Cntr=.5,.3

Type RM Length L Ch R = 2 ,5117    ,,,
BEGIN DESCRIPTION:
5103  cook (2) 7'x10'
END DESCRIPTION:
Bridge Culvert--1,0,-1,-1, 0
Deck Dist Width WeirC Skew NumUp NumDn MinLoCord MaxHiCord MaxSubmerge Is_Ogee
14.255,42,2.6,0, 7, 7, , , .95, 0, 0,0,,
    2600 2644.35 2683.24 2722.69 2762.14 2769.29 2824.81
   74.86   77.01   77.01   77.11   77.03   77.03   75.08
               0       0       0       0       0
    2600 2672.24 2711.13 2750.58 2790.03 2797.18 2824.81
   74.87   77.01   77.01   77.11   77.03   77.03   75.63
               0       0       0       0       0
BR Coef=-1 , 0 , 0 ,, 0 ,,,.8,-1,,0,
WSPro=,,,, 1 ,,,, 0 ,,,, 0 ,,,,-1 ,-1 ,-1 , 0 , 0 , 0 , 0 , 0
Culvert=2,7,10,42,.012,.5,1,8,3,59.24,2682.42,59.04,2710.42,Culvert #1  , 0 ,14.255
Culvert Bottom n=.012
Culvert=2,7,10,42,.012,.5,1,8,2,59.24,2692.42,59.04,2720.42,Culvert #2  , 0 ,14.255
Culvert Bottom n=.012
BC Design=,, 0 ,, 0 ,,,,,,

Type RM Length L Ch R = 1 ,5081    ,63.15,68.78,77.01
BEGIN DESCRIPTION:
5067  Surveyed cross-section/XS2
END DESCRIPTION:
XS GIS Cut Line= 4
     3048757.773    13823136.362     3048887.301    13820473.173
     3048888.312    13820341.783     3048948.591     13819097.74
#Sta/Elev= 30
       0   74.61   12.97   75.04   84.58   73.93  224.13   74.65  356.68   73.65
  528.54   74.93   843.6   74.57  857.92   73.92  929.53   75.11 1087.06   75.43
 1230.28    74.8 1650.81   74.88 1831.02   75.59  1891.1   74.42  1989.3   74.08
 2218.44   75.34    2657   74.65 2666.34   75.89 2677.26    75.9 2705.15   62.47
 2706.59   60.58 2715.42    59.8 2725.26   60.76 2727.03   62.57 2797.73   75.31
 3140.04   76.18 3182.47   75.21 3632.99   74.36 3956.48   75.13 4043.23   76.14
#Mann= 3 , 0 , 0
       0      .1       0 2677.26     .04       0 2797.73     .15       0
#XS Ineff= 2 , 0
       0    2482            2850       0
Permanent Ineff=
       T       T
Bank Sta=2677.26,2797.73
XS Rating Curve= 0
Exp/Cntr=.5,.3

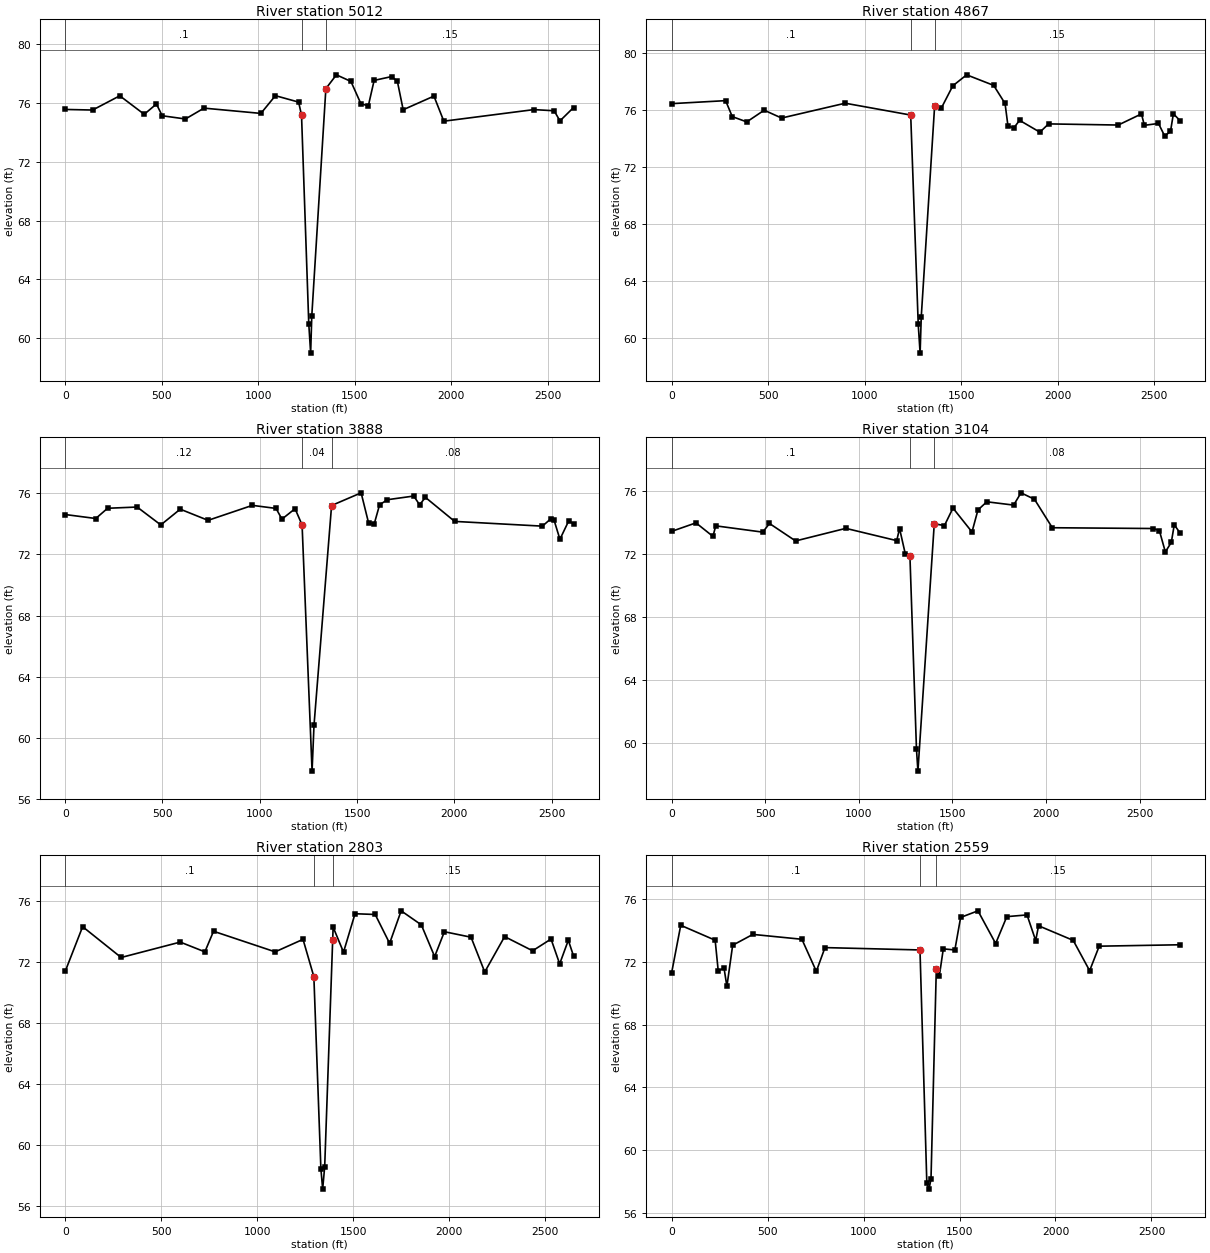
Type RM Length L Ch R = 1 ,5012    ,144.72,145.4,145.97
BEGIN DESCRIPTION:
4998  Copied surveyed cross-section 5067/XS1
END DESCRIPTION:
XS GIS Cut Line= 6
     3048867.678     13821703.94     3048951.822      13820471.3
     3048952.601     13820462.31     3048957.399     13820407.72
     3048963.347      13820339.6     3049057.219    13819077.348
#Sta/Elev= 30
       0   75.57  141.93   75.53  282.67    76.5  409.33   75.24  472.54   75.94
  502.61   75.14  622.89   74.92  718.97   75.66 1013.79    75.3 1088.97   76.51
 1209.25   76.07 1224.28   75.18 1261.78   60.97 1271.53   58.96 1277.49   61.51
  1350.4   76.99 1404.91   77.93 1480.12   77.48 1532.22   75.95 1570.37   75.82
 1600.45   77.55  1690.7   77.81 1720.78   77.49 1750.87   75.55 1910.22   76.48
 1961.45   74.77 2428.23   75.56 2533.02   75.48  2563.1   74.79 2633.45    75.7
#Mann= 3 , 0 , 0
       0      .1       0 1224.28     .04       0  1350.4     .15       0
#XS Ineff= 2 , 0
       0    1052            1378       0
Permanent Ineff=
       T       T
Bank Sta=1224.28,1350.4
XS Rating Curve= 0
Exp/Cntr=.3,.1

Type RM Length L Ch R = 1 ,4867    ,975.54,979.23,977.76
BEGIN DESCRIPTION:
4853  Surveyed cross-section
END DESCRIPTION:
XS GIS Cut Line= 4
     3049013.076    13821710.829     3049096.011    13820482.441
     3049108.733    13820351.361     3049202.703    13819083.326
#Sta/Elev= 30
       0   76.45  279.56   76.66  314.04   75.54  389.21   75.17  479.42   75.99
  569.62   75.44  899.22   76.48 1238.79   75.65 1277.78   60.97 1287.53   58.96
 1293.49   61.51 1362.88   76.31 1396.83   76.12    1457    77.7 1528.71   78.47
 1668.74   77.73 1727.74   76.46 1742.78   74.89 1772.86   74.74 1802.95   75.28
 1908.23   74.45 1953.36   75.03 2314.34   74.95 2434.67   75.73 2449.71   74.93
 2522.95   75.06    2555   74.18 2585.09    74.5 2600.13   75.74 2634.39   75.26
#Mann= 3 , 0 , 0
       0      .1       0 1238.79     .04       0 1362.88     .15       0
#XS Ineff= 2 , 0
       0    1074            1388       0
Permanent Ineff=
       T       T
Bank Sta=1238.79,1362.88
XS Rating Curve= 0
Exp/Cntr=.3,.1

Type RM Length L Ch R = 1 ,3888    ,774.1,783.31,736.7
BEGIN DESCRIPTION:
3874  Surveyed cross-section
END DESCRIPTION:
XS GIS Cut Line= 4
     3049886.398    13821717.663     3050073.246    13820536.164
     3050088.527    13820364.072     3050159.966    13819122.658
#Sta/Elev= 30
       0   74.61  157.09   74.35  217.84   75.02   369.7    75.1  491.19   73.93
  591.18   74.96  734.18   74.23  961.97   75.21 1083.46   75.01 1113.84   74.31
 1181.25   74.99 1217.39   73.93  1268.7   57.82 1278.58   60.81 1368.95    75.2
 1520.77   76.03  1558.9   74.07 1587.31   73.96 1615.73   75.25    1656   75.58
 1791.22   75.82 1821.27   75.25 1851.32   75.73 2001.57   74.16 2452.31   73.85
 2496.58   74.34 2512.41   74.24 2542.46   72.99 2587.54   74.19 2612.42      74
#Mann= 3 , 0 , 0
       0     .12       0 1217.39     .04       0 1368.95     .08       0
#XS Ineff= 2 , 0
       0    1190            1598       0
Permanent Ineff=
       T       T
Bank Sta=1217.39,1368.95
XS Rating Curve= 0
Exp/Cntr=.3,.1

Type RM Length L Ch R = 1 ,3104    ,304.51,301.64,345.84
BEGIN DESCRIPTION:
3090  Surveyed cross-section
END DESCRIPTION:
XS GIS Cut Line= 4
     3050700.939    13821766.361     3050849.318    13820515.803
      3050860.48    13820372.786     3050427.094    13819133.634
#Sta/Elev= 30
       0   73.44  129.76   73.98   220.4   73.12   235.5   73.79  486.49   73.39
   522.5   73.94  662.03   72.83  930.34   73.63 1202.24   72.85 1217.34   73.62
 1247.55   72.03  1272.8   71.87 1307.77   59.58 1315.48   58.19 1402.78   73.92
 1457.25   73.81 1502.68   74.92 1604.37    73.4 1636.15    74.8  1683.5   75.32
 1826.84   75.11 1866.17   75.89 1938.08   75.48 2033.43   73.67 2573.72   73.62
  2605.5   73.48 2637.28   72.13 2669.06   72.74 2684.95   73.86 2715.54   73.34
#Mann= 3 , 0 , 0
       0      .1       0  1272.8     .04       0 1402.78     .08       0
#XS Ineff= 2 , 0
       0    1235            1444       0
Permanent Ineff=
       T       T
Bank Sta=1272.8,1402.78
XS Rating Curve= 0
Exp/Cntr=.3,.1

Type RM Length L Ch R = 1 ,2803    ,244.08,243.77,249.25
BEGIN DESCRIPTION:
2789  Surveyed cross-section
END DESCRIPTION:
XS GIS Cut Line= 4
     3051066.743     13821808.13     3051149.617    13820526.552
     3051163.507    13820385.728     3051199.602    13819165.374
#Sta/Elev= 30
       0   71.36   90.72   74.29  291.24   72.27  598.98   73.28  727.15   72.64
  772.24   73.99 1093.13   72.64 1238.21   73.46 1294.66   71.01 1331.18   58.43
 1340.44   57.08 1351.01   58.55 1392.63   73.43 1394.97   74.26    1449   72.62
 1509.03   75.14 1614.07   75.09 1689.11    73.2 1749.13   75.33 1854.18   74.41
 1923.49   72.33 1974.23   73.96 2112.97    73.6 2184.32   71.32 2287.87   73.64
 2433.63   72.71 2529.47   73.48 2574.49   71.85 2619.51    73.4 2646.65   72.37
#Mann= 3 , 0 , 0
       0      .1       0 1294.66     .04       0 1392.63     .15       0
#XS Ineff= 2 , 0
       0    1200            1437       0
Permanent Ineff=
       T       T
Bank Sta=1294.66,1392.63
XS Rating Curve= 0
Exp/Cntr=.3,.1

Type RM Length L Ch R = 1 ,2559    ,56.01,56.05,56.01
BEGIN DESCRIPTION:
2545  Copied surveyed cross-section 2789/XS4
END DESCRIPTION:
XS GIS Cut Line= 6
     3051308.528    13821819.586     3051392.838     13820548.95
     3051400.364     13820462.73     3051402.789     13820435.18
     3051404.494     13820415.54     3051497.296    13819177.606
#Sta/Elev= 30
       0   71.31   47.19   74.32  226.56   73.37  242.62   71.41  272.68   71.61
  287.72   70.43  317.78   73.05  423.01   73.74  678.57   73.43  753.74   71.39
  798.84    72.9 1293.89   72.75 1329.59    57.9 1340.69   57.53 1351.23   58.16
 1378.93   71.53 1394.46   71.08 1415.41   72.82 1475.58   72.75 1505.66   74.82
 1595.92   75.24 1688.19   73.16 1746.34   74.87 1851.63   74.98 1896.76   73.35
  1911.8   74.29  2092.3   73.36 2177.94   71.43 2227.68   72.99 2648.76   73.08
#Mann= 3 , 0 , 0
       0      .1       0 1293.89     .04       0 1378.93     .15       0
#XS Ineff= 2 , 0
       0    1223            1425       0
Permanent Ineff=
       T       T
Bank Sta=1293.89,1378.93
XS Rating Curve= 0
Exp/Cntr=.5,.3

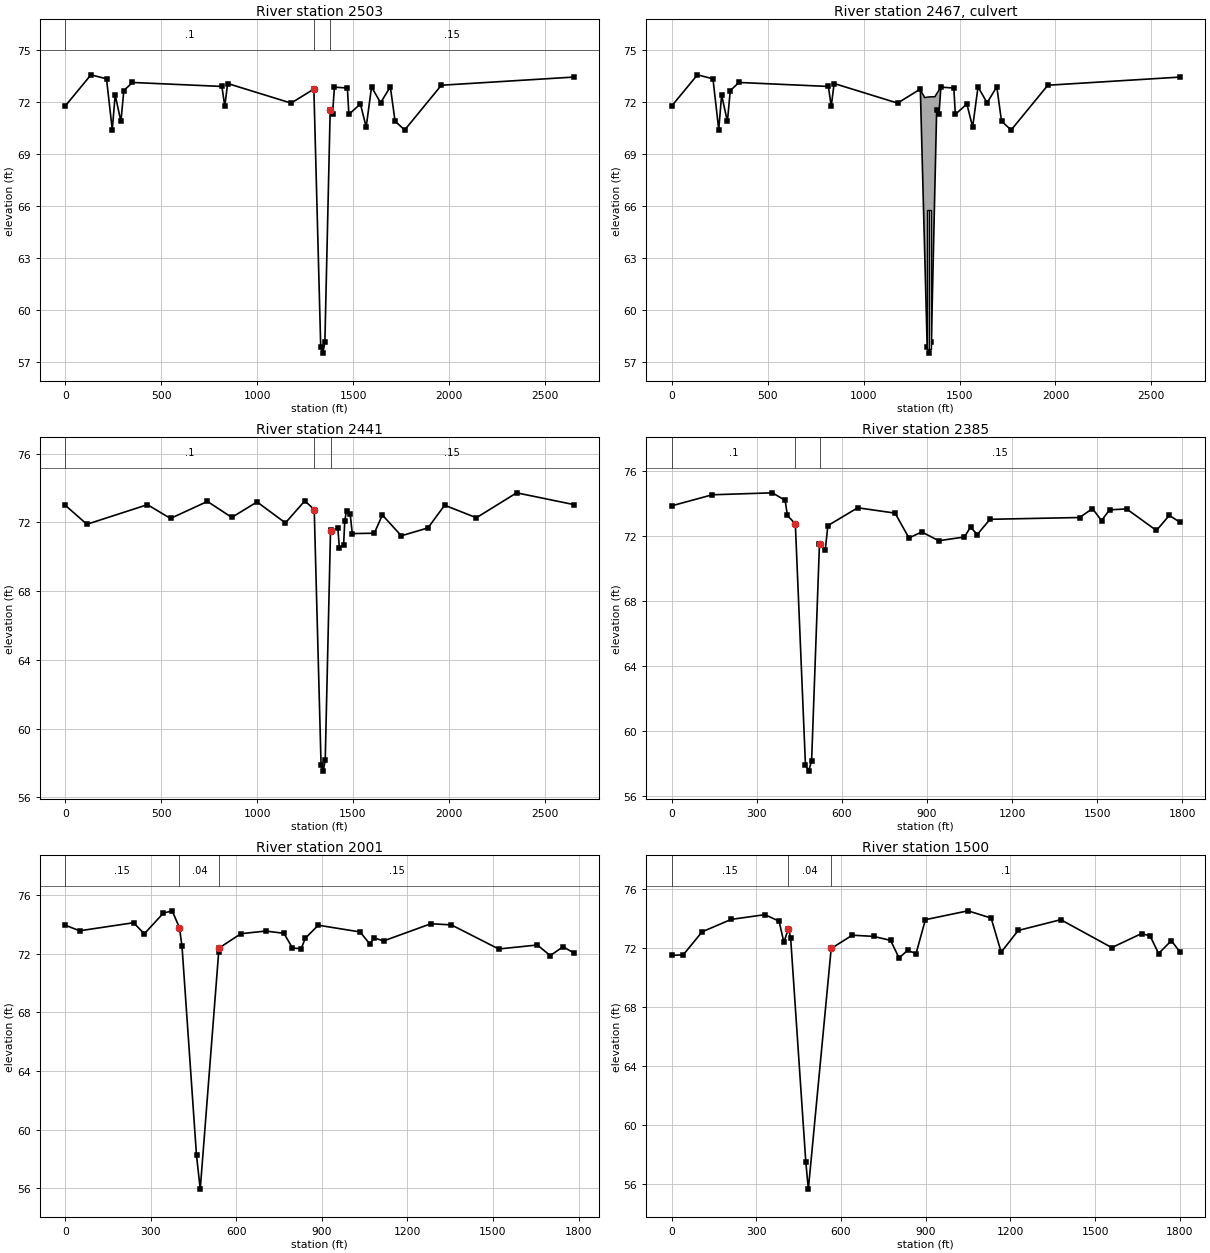
Type RM Length L Ch R = 1 ,2503    ,62.1,62.39,62.45
BEGIN DESCRIPTION:
2489  Copied surveyed cross-section 2789/XS3
END DESCRIPTION:
XS GIS Cut Line= 6
     3051364.478    13821822.237     3051448.677     13820553.24
     3051455.226     13820478.19     3051458.576     13820440.06
     3051460.313     13820420.05     3051553.282    13819179.906
#Sta/Elev= 30
       0   71.77  134.17   73.57  215.21   73.34  245.28   70.41  260.31   72.41
  290.37   70.88  305.41   72.66  350.51   73.13  816.53    72.9  831.56   71.76
  846.59   73.07 1177.32   71.94 1295.89   72.75 1331.59    57.9 1342.69   57.53
 1353.23   58.16 1380.93   71.53 1393.07   71.31 1403.03   72.86 1470.54   72.81
 1478.24   71.29 1538.41   71.89 1568.49   70.56 1596.48   72.87  1643.7   71.96
 1694.43   72.88 1718.91    70.9 1769.16   70.39  1960.3   72.97 2649.11   73.44
#Mann= 3 , 0 , 0
       0      .1       0 1295.89     .04       0 1380.93     .15       0
#XS Ineff= 2 , 0
       0    1232            1422       0
Permanent Ineff=
       T       T
Bank Sta=1295.89,1380.93
XS Rating Curve= 0
Exp/Cntr=.5,.3

Type RM Length L Ch R = 2 ,2467    ,,,
BEGIN DESCRIPTION:
2453  kirkwood (2) 8'x10'
END DESCRIPTION:
Bridge Culvert--1,0,-1,-1, 0
Deck Dist Width WeirC Skew NumUp NumDn MinLoCord MaxHiCord MaxSubmerge Is_Ogee
10.39,30,2.6,0, 7, 7, 72.7, , .95, 0, 0,0,,
 1295.98 1315.22 1316.78 1344.78 1372.78 1374.33  1403.3
   72.68   72.34   72.26    72.3   72.31   72.36   72.87
                                                        
 1297.84 1317.22 1318.78 1346.78 1374.78 1376.33 1384.43
   72.68   72.34   72.26    72.3   72.31   72.36    71.5
                                                        
BR Coef=-1 , 0 , 0 ,, 0 ,,,.8,-1,,0,
WSPro=,,,, 1 ,,,, 0 ,,,, 0 ,,,,-1 ,-1 ,-1 , 0 , 0 , 0 , 0 , 0
Multiple Barrel Culv=2,8,10,52,.012,.5,1,8,3,57.79,57.6, 2,Culvert #1  , 0 ,1
 1336.91 1338.91 1347.91 1345.91
Culvert Bottom n=.012
BC Design=,, 0 ,, 0 ,,,,,,

Type RM Length L Ch R = 1 ,2441    ,55.91,55.72,55.72
BEGIN DESCRIPTION:
2426  Surveyed cross-section/XS2
END DESCRIPTION:
XS GIS Cut Line= 4
     3051426.425    13821825.172     3051510.601    13820557.998
     3051522.597    13820425.093     3051615.264    13819182.453
#Sta/Elev= 30
       0      73  112.92   71.89  428.61   73.03  548.88   72.23  741.25   73.22
  868.12   72.29  999.87   73.19 1147.75   71.97 1248.73   73.25 1297.89   72.75
 1333.59    57.9 1344.69   57.53 1355.23   58.16 1382.93   71.53 1384.42    71.5
 1421.05   71.67 1429.07    70.5 1451.14    70.7 1457.07   72.08 1466.18   72.69
 1485.06   72.51 1496.26   71.35 1611.04   71.37 1653.04   72.43 1751.97   71.22
    1891   71.68  1977.6      73 2143.05   72.27 2352.93   73.72  2649.5   73.04
#Mann= 3 , 0 , 0
       0      .1       0 1297.89     .04       0 1384.42     .15       0
#XS Ineff= 2 , 0
       0    1243            1418       0
Permanent Ineff=
       T       T
Bank Sta=1297.89,1384.42
XS Rating Curve= 0
Exp/Cntr=.5,.3

Type RM Length L Ch R = 1 ,2385    ,378.83,383.71,380.73
BEGIN DESCRIPTION:
2371  Copied surveyed cross-section 2426/XS1
END DESCRIPTION:
XS GIS Cut Line= 6
     3051539.181    13820971.552     3051566.337     13820562.28
     3051572.784     13820488.39     3051576.128     13820450.33
     3051577.931     13820429.56     3051671.249    13819184.753
#Sta/Elev= 30
       0   73.87   143.2   74.55  354.83   74.67  399.93   74.21  407.97   73.28
  435.89   72.75  471.59    57.9  482.69   57.53  493.23   58.16  520.93   71.53
  522.42    71.5  541.41   71.15  550.48   72.65  655.77   73.75  787.46   73.42
  836.28   71.89   881.4   72.26  941.39   71.72 1031.82   71.95 1053.33   72.56
 1076.95    72.1 1122.08   73.04 1437.96   73.15 1483.09    73.7  1515.1   72.96
 1543.26   73.62 1603.42   73.68 1708.72   72.35 1753.84   73.28  1791.7   72.86
#Mann= 3 , 0 , 0
       0      .1       0  435.89     .04       0  522.42     .15       0
#XS Ineff= 2 , 0
       0     395             557       0
Permanent Ineff=
       T       T
Bank Sta=435.89,522.42
XS Rating Curve= 0
Exp/Cntr=.3,.1

Type RM Length L Ch R = 1 ,2001    ,481.65,500.87,501.31
BEGIN DESCRIPTION:
1987  Surveyed cross-section
END DESCRIPTION:
XS GIS Cut Line= 4
     3051861.276    13820966.622     3051956.944    13820577.598
     3051955.932    13820440.073      3052070.23    13819201.147
#Sta/Elev= 30
       0   73.93   50.59   73.55  239.98    74.1  277.18   73.34  344.08   74.75
  374.97   74.91  400.61   73.76  409.57   72.48  460.36   58.24  473.45   55.94
  538.14    72.1  540.73   72.39  616.05   73.35  702.85   73.53  766.68   73.38
  796.81   72.38  826.97   72.32     842   73.04  887.19   73.93 1033.84   73.47
 1067.96   72.65 1083.02   73.06 1116.59   72.86 1282.09   74.03 1354.17   73.95
 1519.87   72.31 1655.44   72.58 1700.63   71.86 1745.82   72.46 1782.33   72.05
#Mann= 3 , 0 , 0
       0     .15       0  400.61     .04       0  540.73     .15       0
#XS Ineff= 2 , 0
       0     394             541       0
Permanent Ineff=
       T       T
Bank Sta=400.61,540.73
XS Rating Curve= 0
Exp/Cntr=.3,.1

Type RM Length L Ch R = 1 ,1500    ,321.26,315.01,312.33
BEGIN DESCRIPTION:
1486  Surveyed cross-section
END DESCRIPTION:
XS GIS Cut Line= 4
     3052263.366    13820969.111     3052456.446    13820603.067
     3052456.446    13820451.755     3052579.547    13819222.074
#Sta/Elev= 30
       0   71.49   41.39   71.54  107.88   73.09  210.98   73.93  330.37   74.25
  380.57   73.81  397.53   72.38  413.85   73.31  421.42    72.7  475.16   57.52
  484.22   55.67  565.16   71.96  639.78   72.86  715.16   72.78  775.55   72.51
  805.61   71.32  835.76   71.83  865.91   71.62  898.88   73.91 1049.62   74.51
 1131.84   74.02 1167.41   71.71 1227.71   73.18 1378.46   73.91 1559.36   72.02
 1664.88   72.97 1695.03   72.81 1725.18   71.62 1770.41   72.49 1800.98   71.72
#Mann= 3 , 0 , 0
       0     .15       0  413.85     .04       0  565.16      .1       0
#XS Ineff= 2 , 0
       0     410             577       0
Permanent Ineff=
       T       T
Bank Sta=413.85,565.16
XS Rating Curve= 0
Exp/Cntr=.3,.1

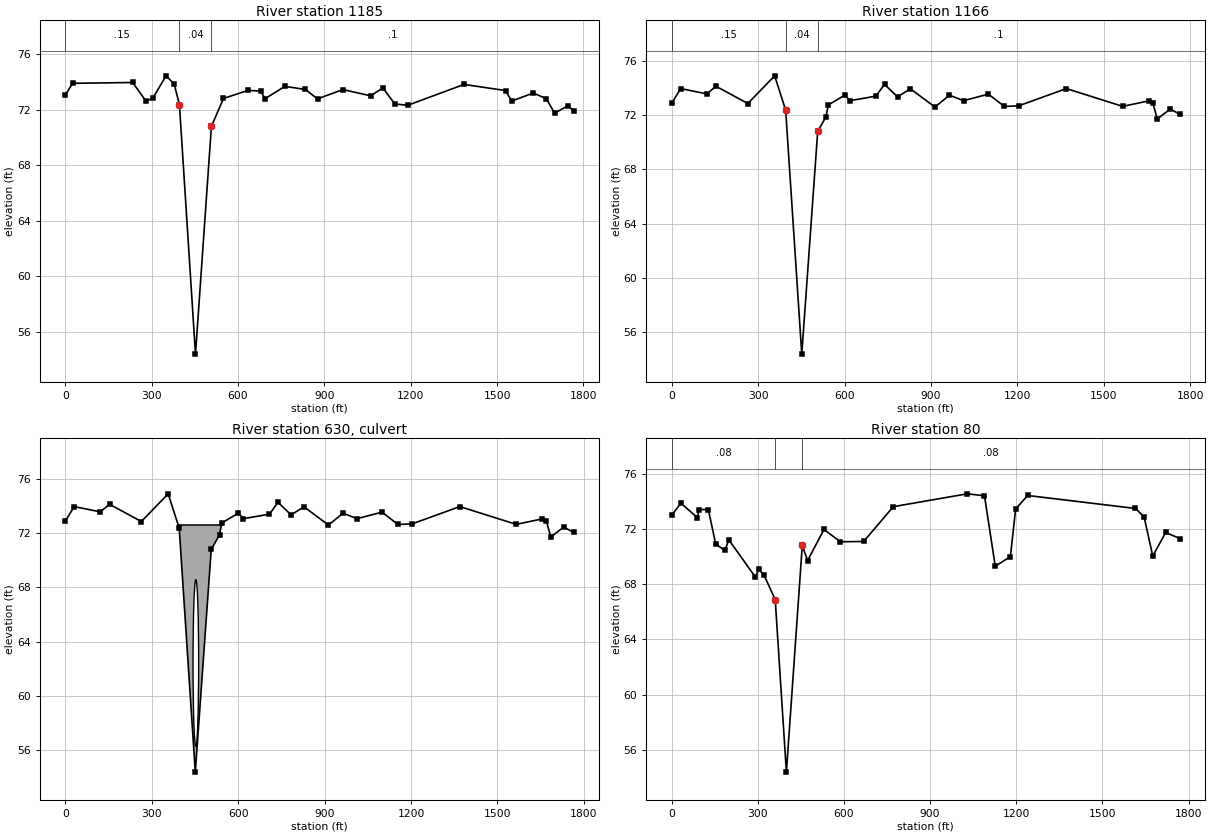
Type RM Length L Ch R = 1 ,1185    ,20.19,19.48,20.03
BEGIN DESCRIPTION:
1171  Copied surveyed cross-section 1152/XS4
END DESCRIPTION:
XS GIS Cut Line= 6
     3052634.848     13820971.41     3052770.843      13820612.3
     3052770.843     13820600.18     3052770.843     13820544.37
     3052770.843     13820459.77     3052842.298    13819232.869
#Sta/Elev= 30
       0   73.04   25.57    73.9  234.08   73.96  280.42   72.63  303.69   72.81
  350.23   74.44  378.44   73.86  396.67   72.37  452.48   54.39  507.79    70.8
  549.71   72.81   634.9   73.39  679.04   73.34  694.06   72.79  762.69   73.68
  833.68   73.46  876.28   72.78  964.52   73.45 1060.86      73 1103.45   73.57
 1144.83   72.41  1189.9   72.32 1385.23   73.82 1529.41   73.38 1550.51   72.62
 1625.64    73.2 1670.72    72.8 1699.79   71.75 1745.84   72.28 1765.51   71.93
#Mann= 3 , 0 , 0
       0     .15       0  396.67     .04       0  507.79      .1       0
#XS Ineff= 2 , 0
       0     374             535       0
Permanent Ineff=
       T       T
Bank Sta=396.67,507.79
XS Rating Curve= 0
Exp/Cntr=.5,.3

Type RM Length L Ch R = 1 ,1166    ,962.27,1085.96,1085.35
BEGIN DESCRIPTION:
1152  Surveyed cross-section/XS3
END DESCRIPTION:
XS GIS Cut Line= 4
     3052656.193    13820971.542     3052789.884    13820615.955
      3052790.87    13820460.351     3052862.284    13819233.691
#Sta/Elev= 30
       0   72.88   31.33   73.96  121.84   73.57  153.89   74.13  264.26   72.86
  357.43    74.9  395.67   72.37  451.48   54.39  506.79    70.8   535.5   71.88
  543.36   72.75  601.27   73.48  618.49   73.07  708.64    73.4  738.69   74.27
  783.77   73.35  828.84   73.94  913.64    72.6  964.07   73.47 1013.03   73.07
  1099.3   73.55 1155.02   72.64 1204.48   72.69 1369.76   73.96 1565.09   72.65
 1655.24   73.05 1670.27   72.87 1685.29   71.72 1730.37   72.45 1764.23   72.06
#Mann= 3 , 0 , 0
       0     .15       0  395.67     .04       0  506.79      .1       0
#XS Ineff= 2 , 0
       0     373             532       0
Permanent Ineff=
       T       T
Bank Sta=395.67,506.79
XS Rating Curve= 0
Exp/Cntr=.5,.3

Type RM Length L Ch R = 2 ,630     ,,,
BEGIN DESCRIPTION:
616
END DESCRIPTION:
Bridge Culvert--1,0,-1,-1, 0
Deck Dist Width WeirC Skew NumUp NumDn MinLoCord MaxHiCord MaxSubmerge Is_Ogee
6.09,1060,2.6,0, 3, 5, 72.6, , .95, 0, 0,0,,
     392  453.38     545
    72.6    72.6    72.6
                        
  240.56  342.73  399.73  462.73  530.56
   70.35    72.6    72.6    72.6   71.97
                                        
Culvert=5,12.3,19.5,1060,.024,.7,1,41,1,56.28,453.38,55.28,399.73,Culvert #1  , 0 ,6.09
Culvert Bottom n=.024
BC Design=,, 0 ,, 0 ,,,,,,

Type RM Length L Ch R = 1 ,80      ,16.71,79.8,15.6
BEGIN DESCRIPTION:
80  Copied surveyed cross-section 1152/XS2
END DESCRIPTION:
XS GIS Cut Line= 3
     3053564.233    13820901.114     3053869.195    13820607.087
     3053947.487    13819262.791
#Sta/Elev= 30
       0   72.99   32.32   73.86   89.73   72.81   94.83    73.4  127.67    73.4
  153.38    70.9  185.21   70.44  199.01   71.21  291.29   68.52  303.19   69.07
  322.17   68.63  360.57   66.88  399.48   54.39  454.79    70.8  473.29   69.71
  530.48   71.96  587.27   71.07  668.62   71.09  771.85   73.61 1029.23   74.54
 1089.33    74.4 1126.82    69.3 1179.49   69.99 1197.81   73.44 1239.59   74.42
 1615.22   73.48 1645.27   72.86 1675.32   70.04  1720.4   71.74 1770.19    71.3
#Mann= 3 , 0 , 0
       0     .08       0  360.57     .04       0  454.79     .08       0
#XS Ineff= 2 , 0
       0     230             601       0
Permanent Ineff=
       T       T
Bank Sta=360.57,454.79
XS Rating Curve= 0
Exp/Cntr=.5,.3

Chan Stop Cuts=-1